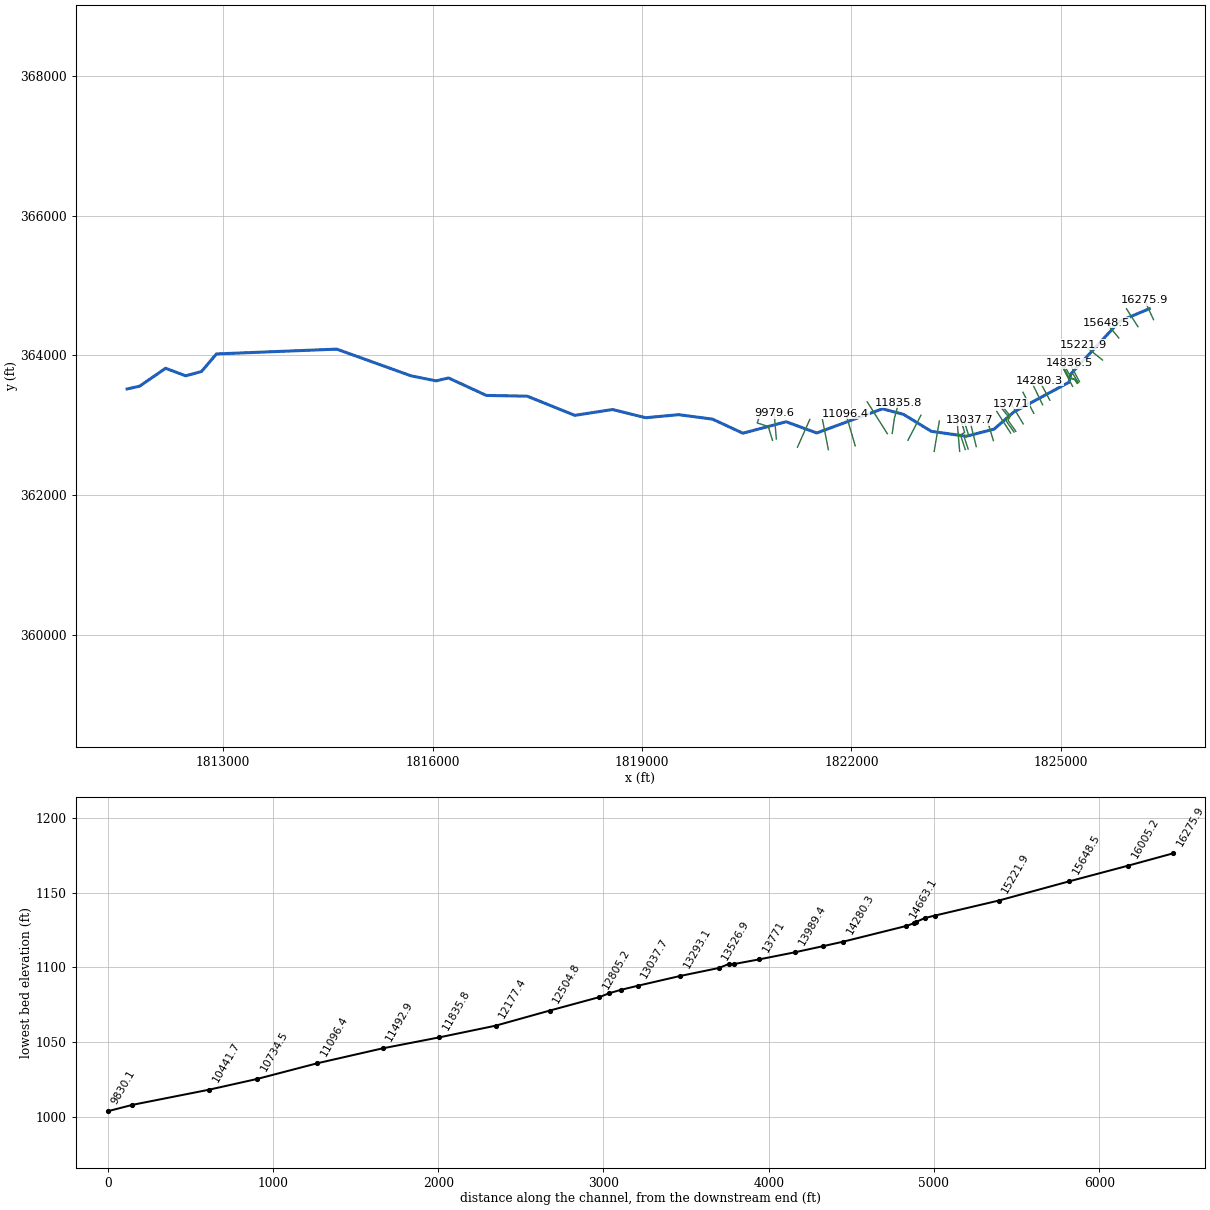
--- SENGCK.prj (project) ---

Proj Title=SENGCK
Current Plan=p01
Default Exp/Contr=0,0
English Units
Geom File=g01
Flow File=f01
Plan File=p01
BEGIN DESCRIPTION:
END DESCRIPTION:
DSS Export Rating Curves= 0
DSS Export Rating Curve Sorted= 0
DSS Export Volume Flow Curves= 0
DXF OffsetX= 0
DXF OffsetY= 0
DXF ScaleX= 0
DXF ScaleY= 0

--- SENGCK.p01 (plan) ---

Plan Title=Floodplain
Program Version=4.00
Geom File=g01
Flow File=f01
K Sum by GR=0
Std Step Tol=0.01
Critical Tol=0.01
Num of Std Step Trials=20
Max Error Tol=0.3
Flow Tol Ratio=0.001
Split Flow NTrial=30
Split Flow Tol=0.02
Split Flow Ratio=0.02
Log Output Level=0
Friction Slope Method=1
Unsteady Friction Slope Method=2
Unsteady Bridges Friction Slope Method=1
Global Log Level=0
CheckData=False
Run HTab=0
Run UNet=0
Run PostProcess=0
UNET Theta=0
UNET Theta Warmup=0
UNET ZTol=0
UNET ZSATol=0
UNET MxIter=0
UNET MaxInSteps=0
UNET DtIC=0
UNET DtMin=0
UNET MaxCRTS=0
UNET WFStab=0
UNET SFStab=0
UNET WFX=0
UNET SFX=0
UNET DSS MLevel=0
UNET DZMax Abort=0
UNET Convert EG Bridges=0
UNET Use Existing IB Tables=0
UNET Froude Limit=0
UNET Froude Power=0
Write IC File=0
Echo Input=False
Echo Output=False
Write Detailed=0

--- SENGCK.f01 (steady flow) ---

Flow Title=NFF Regression Equation
Program Version=4.10
Number of Profiles= 1
Profile Names=P100yr
River Rch & RM=SENGCK,Main            ,16275.9
863.9546
River Rch & RM=SENGCK,Main            ,14836.5
914.6448
River Rch & RM=SENGCK,Main            ,14663.1
1159.254
River Rch & RM=SENGCK,Main            ,13989.4
1167.271
River Rch & RM=SENGCK,Main            ,11492.9
1290.262
River Rch & RM=SENGCK,Main            ,11096.4
1347.421
River Rch & RM=SENGCK,Main            ,8409.2
1447.027
River Rch & RM=SENGCK,Main            ,5157.3
 1606.87
River Rch & RM=SENGCK,Main            ,570.8
1758.659
Boundary for River Rch & Prof#=SENGCK,Main            , 1
Up Type= 0
Dn Type= 3
Dn Slope=0.01648
DSS Import GetInterval= 0
DSS Import GetPeak= 0
DSS Import FillOption= 0

--- SENGCK.g01 (geometry) ---

Geom Title=USGS 10m DEM
Program Version=4.10

River Reach=SENGCK          ,Main
Reach XY= 30
     1826265.872      364668.294      1825843.38       364490.43
     1825140.708      363732.807     1825117.792      363616.835
     1824324.736      363189.752     1824044.875      362946.002
     1823645.569      362843.224     1823144.181      362914.058
     1822746.264      363156.419     1822444.181       363236.28
     1821503.208      362890.447     1821065.014      363050.863
     1820444.875      362886.974     1820010.153      363088.363
      1819525.43      363152.252     1819053.903      363108.502
     1818577.514      363225.863     1818037.236       363142.53
      1817356.68      363416.836     1816769.875      363427.946
     1816227.466      363677.913      1816050.43       363636.28
     1815692.792      363707.807     1814626.819      364090.516
     1812903.903      364021.766      1812689.32      363769.752
     1812463.625      363708.641     1812175.431       363816.28
     1811803.208       363560.03     1811624.042      363520.446

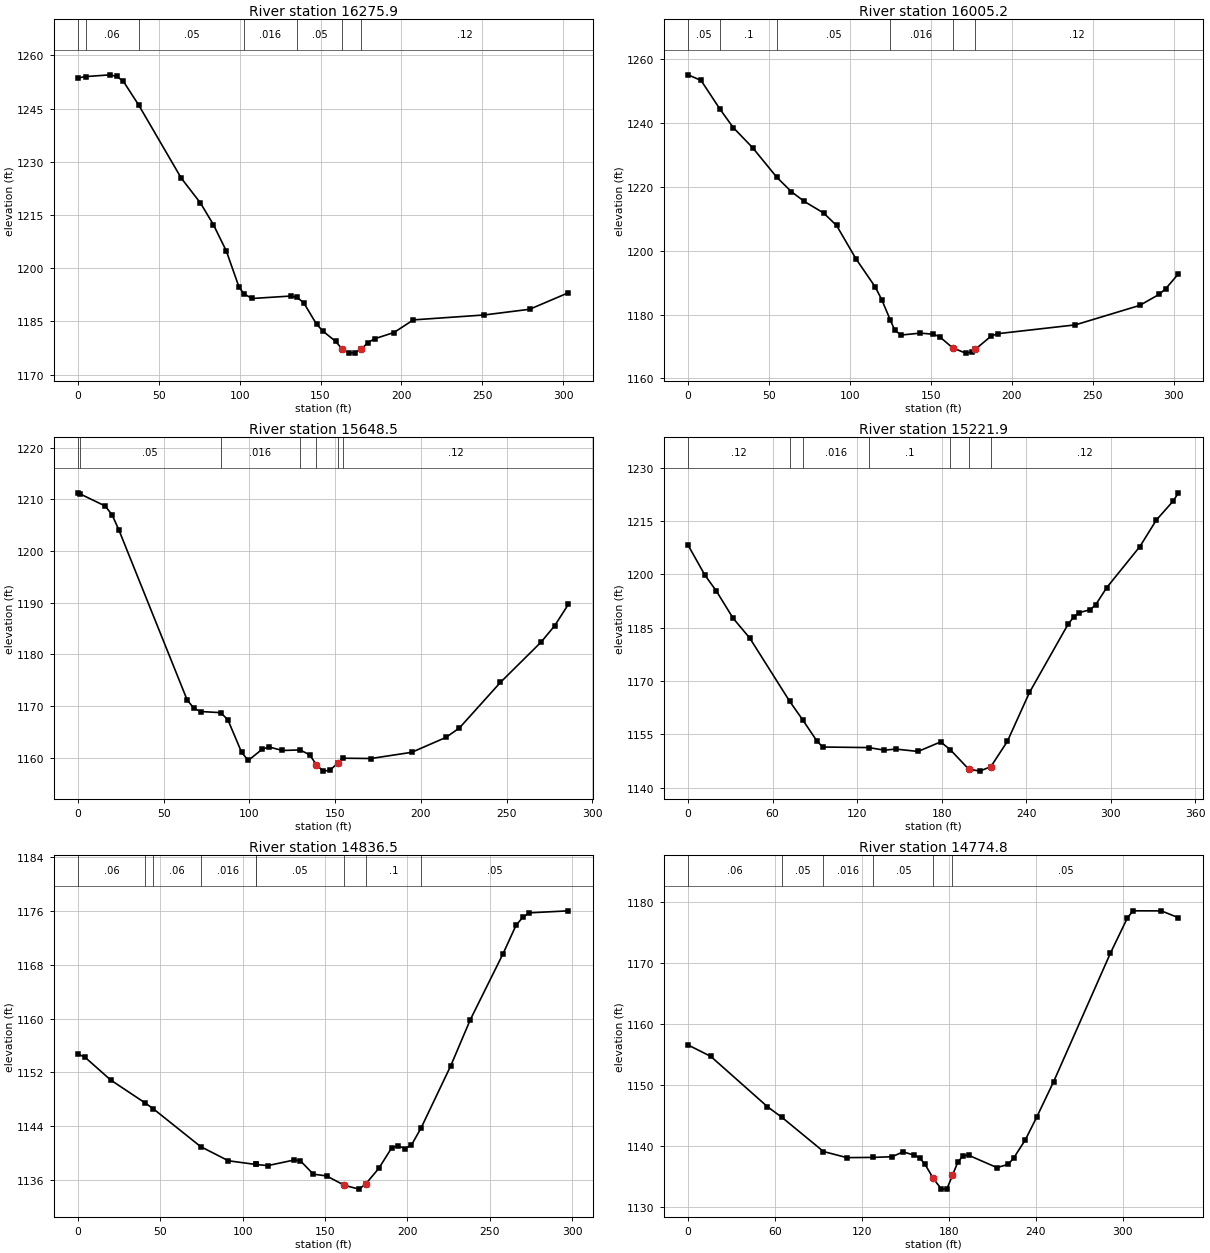
Type RM Length L Ch R = 1 ,16275.9 ,267.7,270.7,274.3
XS GIS Cut Line= 3
     1826327.661      364512.784     1826256.662      364664.397
     1826203.726      364789.519
#Sta/Elev= 30
       0 1253.67    4.831254.031    19.9 1254.53    23.9 1254.06    27.9 1252.78
   37.44 1246.06    63.8 1225.43    75.7  1218.4    83.7 1212.31    91.7 1204.88
    99.6 1194.65  102.671192.777   107.6 1191.48   131.5 1192.17  135.291191.819
   139.5 1190.34   147.5 1184.24   151.5 1182.27   159.4 1179.36   163.4 1177.18
   167.4 1176.08   171.4 1176.24   174.9 1177.12   179.4 1179.06   183.4 1180.12
   195.4 1181.89   207.4 1185.45   251.3 1186.84   279.3 1188.44   303.3  1193.1
#Mann= 7 ,-1 , 0
       0      .1       0    4.83     .06       0   37.44     .05       0
  102.67    .016       0  135.29     .05       0   163.4    .045       0
   174.9     .12       0
Bank Sta=163.4,174.9
XS Rating Curve= 0 ,0
Exp/Cntr=0.3,0.1

Type RM Length L Ch R = 1 ,16005.2 ,353.4,356.7,360.1
XS GIS Cut Line= 2
     1826104.297      364411.976     1825941.103      364667.184
#Sta/Elev= 30
       0 1255.06       8  1253.3   19.681244.307    27.9 1238.53    39.9 1232.21
   54.741223.001    63.8 1218.46    71.8  1215.4    83.7 1211.79    91.7 1207.88
   103.6 1197.51   115.6 1188.61   119.6 1184.66  124.861178.308   127.6 1175.15
   131.5 1173.57   143.5 1174.18   151.5 1173.82   155.4 1173.04   163.4 1169.56
   171.4 1167.91   175.4 1168.22   177.3 1169.06   187.3 1173.29   191.3    1174
   239.2 1176.76     279 1182.86     291 1186.33     295 1188.08   302.9 1192.75
#Mann= 6 ,-1 , 0
       0     .05       0   19.68      .1       0   54.74     .05       0
  124.86    .016       0   163.4    .045       0   177.3     .12       0
Bank Sta=163.4,177.3
XS Rating Curve= 0 ,0
Exp/Cntr=0.3,0.1

Type RM Length L Ch R = 1 ,15648.5 ,422.1,426.6,430.8
XS GIS Cut Line= 2
     1825829.991      364250.517       1825647.7      364471.003
#Sta/Elev= 30
       0 1211.24    1.071211.045    15.9 1208.68    19.9 1206.95    23.8 1204.08
    63.6 1171.25    67.6 1169.58    71.5 1168.97   83.191168.753    87.4 1167.38
    95.4  1161.1    99.3 1159.51   107.3 1161.65   111.3 1162.13   119.2 1161.44
  129.541161.546   135.1 1160.61   139.1 1158.68     143 1157.45     147 1157.62
   151.4 1158.98  154.371159.945   170.9 1159.89   194.7 1161.09   214.6 1163.96
   222.5 1165.79   246.4 1174.59   270.2  1182.4   278.1 1185.56   286.1  1189.7
#Mann= 7 ,-1 , 0
       0      .1       0    1.07     .05       0   83.19    .016       0
  129.54     .06       0   139.1    .045       0   151.4     .06       0
  154.37     .12       0
Bank Sta=139.1,151.4
XS Rating Curve= 0 ,0
Exp/Cntr=0.3,0.1

Type RM Length L Ch R = 1 ,15221.9 ,394.3,385.3,376.3
XS GIS Cut Line= 3
      1825596.72      363934.403     1825435.703      364064.718
     1825326.702      364154.254
#Sta/Elev= 30
       0 1208.24      12 1199.76    19.9 1195.44    31.9 1187.71    43.8 1182.07
   72.09  1164.3   81.251159.123    91.6 1153.02    95.6 1151.41   128.21151.253
   139.4 1150.52   147.4 1150.83   163.3 1150.16   179.3 1152.85  186.081150.685
   199.2  1145.2   207.1 1144.62     215 1145.89   226.7 1153.01   242.4 1166.78
   269.8 1185.99   273.8 1188.03   277.7 1189.26   285.5 1190.08   289.4 1191.48
   297.3 1196.33   320.8 1207.87   332.5 1215.34   344.3 1220.62   348.2    1223
#Mann= 7 ,-1 , 0
       0     .12       0   72.09      .1       0   81.25    .016       0
   128.2      .1       0  186.08     .12       0   199.2    .045       0
     215     .12       0
Bank Sta=199.2,215
XS Rating Curve= 0 ,0
Exp/Cntr=0.3,0.1

Type RM Length L Ch R = 1 ,14836.5 ,36.2,61.8,85.4
XS GIS Cut Line= 2
     1825266.811      363624.562     1825126.186      363887.062
#Sta/Elev= 30
       0  1154.7       4  1154.3    19.8 1150.87   40.911147.422   45.531146.615
   74.411140.963    91.3 1138.85  107.921138.301  108.081138.295   115.2 1138.13
     131 1138.95     135 1138.85   142.9 1136.85   150.9  1136.6   161.8 1135.19
   170.7 1134.63   174.7  1135.4   182.6  1137.7   190.6 1140.82   194.6 1141.06
   198.5 1140.66   202.5 1141.19  208.45 1143.79   226.3 1152.96   238.2 1159.83
   258.1 1169.65     266 1173.89     270 1175.05     274 1175.74   297.8 1176.04
#Mann= 9 ,-1 , 0
       0     .06       0   40.91     .05       0   45.53     .06       0
   74.41    .016       0  107.92     .06       0  108.08     .05       0
   161.8    .045       0   174.7      .1       0  208.45     .05       0
Bank Sta=161.8,174.7
XS Rating Curve= 0 ,0
Exp/Cntr=0.3,0.1

Type RM Length L Ch R = 1 ,14774.8 ,63.4,54.7,48.4
XS GIS Cut Line= 4
     1825249.103      363609.979     1825176.707      363730.812
     1825116.291      363734.458     1825052.228      363855.812
#Sta/Elev= 30
       0 1156.57    15.6 1154.71    54.8 1146.46   64.851144.705   93.471139.121
   109.6 1138.12   127.91138.158   140.9 1138.27   148.4 1139.07     156 1138.53
   159.8 1138.09   163.6 1137.01   169.3 1134.71   174.9 1132.96   178.7    1133
   182.5  1135.2   186.3 1137.42     190 1138.45   193.8  1138.5   213.2 1136.49
     221 1137.01   224.9 1138.09   232.8 1141.01   240.6  1144.7   252.4 1150.57
   291.6 1171.61   303.3 1177.37   307.2 1178.55   326.8 1178.54   338.6 1177.42
#Mann= 6 ,-1 , 0
       0     .06       0   64.85     .05       0   93.47    .016       0
   127.9     .05       0   169.3    .045       0   182.5     .05       0
#XS Ineff= 2 , 0
       0     115             194       0
Permanent Ineff=
       F       F
Bank Sta=169.3,182.5
XS Rating Curve= 0 ,0
Exp/Cntr=0.3,0.1

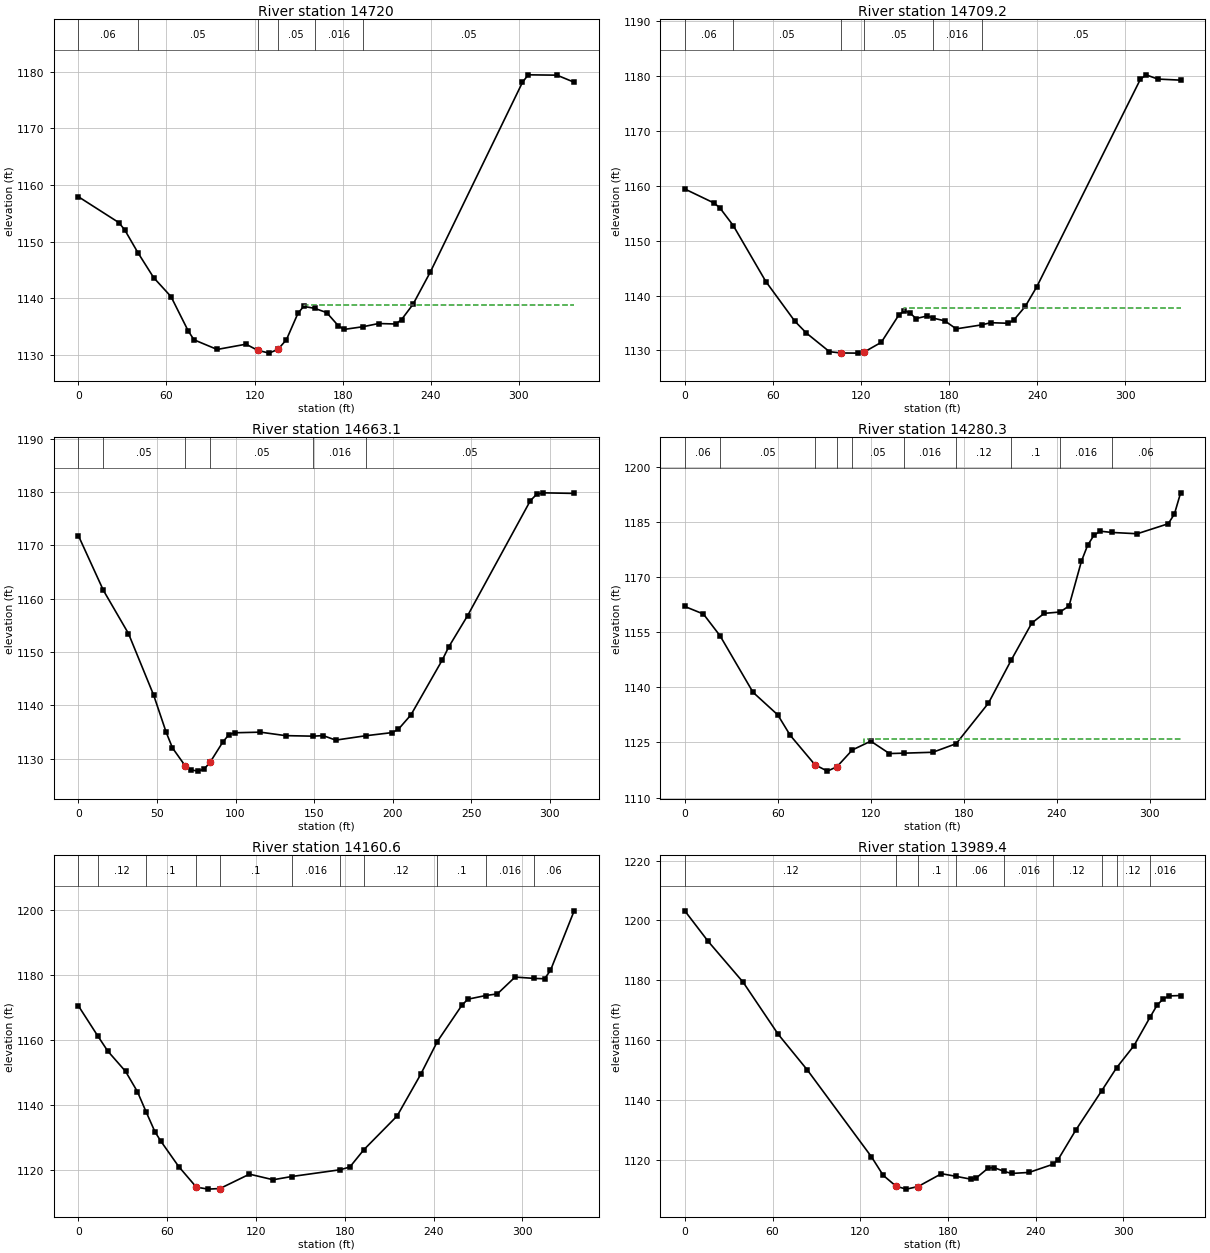
Type RM Length L Ch R = 1 ,14720   ,9.4,10.8,8.9
XS GIS Cut Line= 4
     1825238.166      363606.854      1825203.27      363659.458
     1825113.166      363687.062     1825031.916         363848.
#Sta/Elev= 30
       0 1157.93    27.6 1153.35    31.6 1152.06   40.511148.059    51.3 1143.62
    63.1 1140.27    74.9 1134.16    78.8 1132.63    94.5 1130.93   114.2 1131.86
     122 1130.79   129.9 1130.28     136 1130.96   141.7 1132.66   149.5  1137.3
   153.4 1138.54  160.831138.205   169.1 1137.44     177 1135.12   180.9 1134.47
  193.92 1134.95   204.4 1135.51   216.2 1135.43   220.1 1136.22   227.9 1138.92
   239.7 1144.63   302.4 1178.14   306.3 1179.47   325.9 1179.41   337.6 1178.16
#Mann= 6 ,-1 , 0
       0     .06       0   40.51     .05       0     122    .045       0
     136     .05       0  160.83    .016       0  193.92     .05       0
#XS Ineff= 2 , 0
       0     100          153.51       0 1138.87
Permanent Ineff=
       F       F
Bank Sta=122,136
XS Rating Curve= 0 ,0
Exp/Cntr=0.3,0.1

Type RM Length L Ch R = 1 ,14709.2 ,64,46.1,30.1
XS GIS Cut Line= 4
     1825233.999      363599.562     1825199.103      363652.167
     1825108.999      363679.771     1825027.749      363840.708
#Sta/Elev= 30
       0 1159.41    19.7 1156.88    23.7 1156.03   32.97 1152.76    55.2 1142.55
    74.9 1135.34    82.8 1133.17    98.5 1129.78   106.3 1129.55   118.1 1129.52
     122  1129.7   133.8 1131.49   145.6 1136.41   149.5 1137.26   153.4 1136.83
   157.4 1135.81   165.2  1136.3     1691135.901     177  1135.4   184.8 1133.94
  202.091134.662   208.3 1135.06   220.1 1134.96     224 1135.54   231.8 1138.02
   239.7 1141.62   310.2 1179.39   314.1  1180.2     322 1179.43   337.6 1179.23
#Mann= 6 ,-1 , 0
       0     .06       0   32.97     .05       0   106.3    .045       0
     122     .05       0     169    .016       0  202.09     .05       0
#XS Ineff= 2 , 0
       0      85          149.17       0 1137.74
Permanent Ineff=
       F       F
Bank Sta=106.3,122
XS Rating Curve= 0 ,0
Exp/Cntr=0.3,0.1

Type RM Length L Ch R = 1 ,14663.1 ,382.6,382.8,383
XS GIS Cut Line= 2
     1825168.374      363557.896     1825021.499      363837.062
#Sta/Elev= 30
       0 1171.84   15.951161.559    31.9 1153.47    47.9 1141.95    55.9 1134.96
    59.9 1132.04    67.9 1128.72    71.9 1127.93    75.9  1127.7    79.9 1128.05
    83.8 1129.35    91.8  1133.1    95.8 1134.55    99.8 1134.89   115.8    1135
   131.8 1134.35  149.451134.249   155.7 1134.36   163.7 1133.51  182.83 1134.33
   199.6 1134.92   203.6 1135.55   211.6 1138.25   231.6 1148.57   235.6 1150.96
   247.6 1156.82   287.5 1178.35   291.5 1179.56   295.5 1179.84   315.4 1179.73
#Mann= 6 ,-1 , 0
       0     .06       0   15.95     .05       0    67.9    .045       0
    83.8     .05       0  149.45    .016       0  182.83     .05       0
Bank Sta=67.9,83.8
XS Rating Curve= 0 ,0
Exp/Cntr=0.3,0.1

Type RM Length L Ch R = 1 ,14280.3 ,120.6,119.7,118.8
XS GIS Cut Line= 2
     1824842.506      363358.547     1824691.681      363640.665
#Sta/Elev= 30
       0 1161.97      12 1159.92   22.731154.013      44 1138.64      60 1132.48
      68 1126.94      84 1118.91      92 1117.19    98.2  1118.4   108.11122.951
     120 1125.34     132 1121.97  141.591122.078     160 1122.32  175.081124.655
   195.9 1135.68  210.661147.436   223.9 1157.48   231.9  1160.1  242.071160.462
   247.9 1162.11   255.9 1174.27   259.9 1178.62   263.9 1181.28   267.9 1182.45
  275.561182.103   291.9 1181.75   311.9 1184.47   315.9 1187.12   319.9 1192.88
#Mann= 10 ,-1 , 0
       0     .06       0   22.73     .05       0      84    .045       0
    98.2     .06       0   108.1     .05       0  141.59    .016       0
  175.08     .12       0  210.66      .1       0  242.07    .016       0
  275.56     .06       0
#XS Ineff= 2 , 0
                          115.94         1126.01
Permanent Ineff=
       F       F
Bank Sta=84,98.2
XS Rating Curve= 0 ,0
Exp/Cntr=0.3,0.1

Type RM Length L Ch R = 1 ,14160.6 ,170.7,171.3,171.8
XS GIS Cut Line= 2
     1824738.339      363294.528      1824592.94      363596.177
#Sta/Elev= 30
       0 1170.59   12.951161.436    19.9 1156.65    31.9 1150.42    39.9  1144.2
   45.741138.034    51.8 1131.82    55.8 1128.94    67.8 1121.18    79.7 1114.86
    87.7 1114.25    95.7 1114.44   115.6 1118.85   131.6 1117.13  144.111118.123
   176.91120.203   183.4 1121.05  192.921126.393   215.3 1136.72   231.2 1149.47
  242.471159.587   259.1 1170.76   263.1  1172.6  275.261173.734     283 1174.22
     295  1179.4  308.051178.985   314.9 1178.88   318.9 1181.44   334.9 1199.75
#Mann= 11 ,-1 , 0
       0     .06       0   12.95     .12       0   45.74      .1       0
    79.7    .045       0    95.7      .1       0  144.11    .016       0
   176.9     .05       0  192.92     .12       0  242.47      .1       0
  275.26    .016       0  308.05     .06       0
Bank Sta=79.7,95.7
XS Rating Curve= 0 ,0
Exp/Cntr=0.3,0.1

Type RM Length L Ch R = 1 ,13989.4 ,216.7,218.3,219.6
XS GIS Cut Line= 2
     1824612.471       363170.83     1824457.306      363472.479
#Sta/Elev= 30
       0 1203.18      16 1192.96    39.9 1179.32    63.8 1161.97    83.8 1149.99
   127.7 1120.94   135.7 1114.77   144.6 1111.08   151.6 1110.14   159.6 1111.01
   175.6  1115.3  185.441114.425   195.6 1113.48   199.5 1113.92   207.5 1117.16
   211.5 1117.34  218.661116.045   223.5 1115.38   235.5 1115.72  251.87 1118.45
   255.4 1120.03   267.4 1129.82  285.091142.939  295.391150.713   307.3 1158.11
   318.3 1167.63   323.2 1171.72   327.2 1173.67   331.2 1174.72   339.2 1174.87
#Mann= 9 ,-1 , 0
       0     .12       0   144.6    .045       0   159.6      .1       0
  185.44     .06       0  218.66    .016       0  251.87     .12       0
  285.09      .1       0  295.39     .12       0   318.3    .016       0
Bank Sta=144.6,159.6
XS Rating Curve= 0 ,0
Exp/Cntr=0.3,0.1

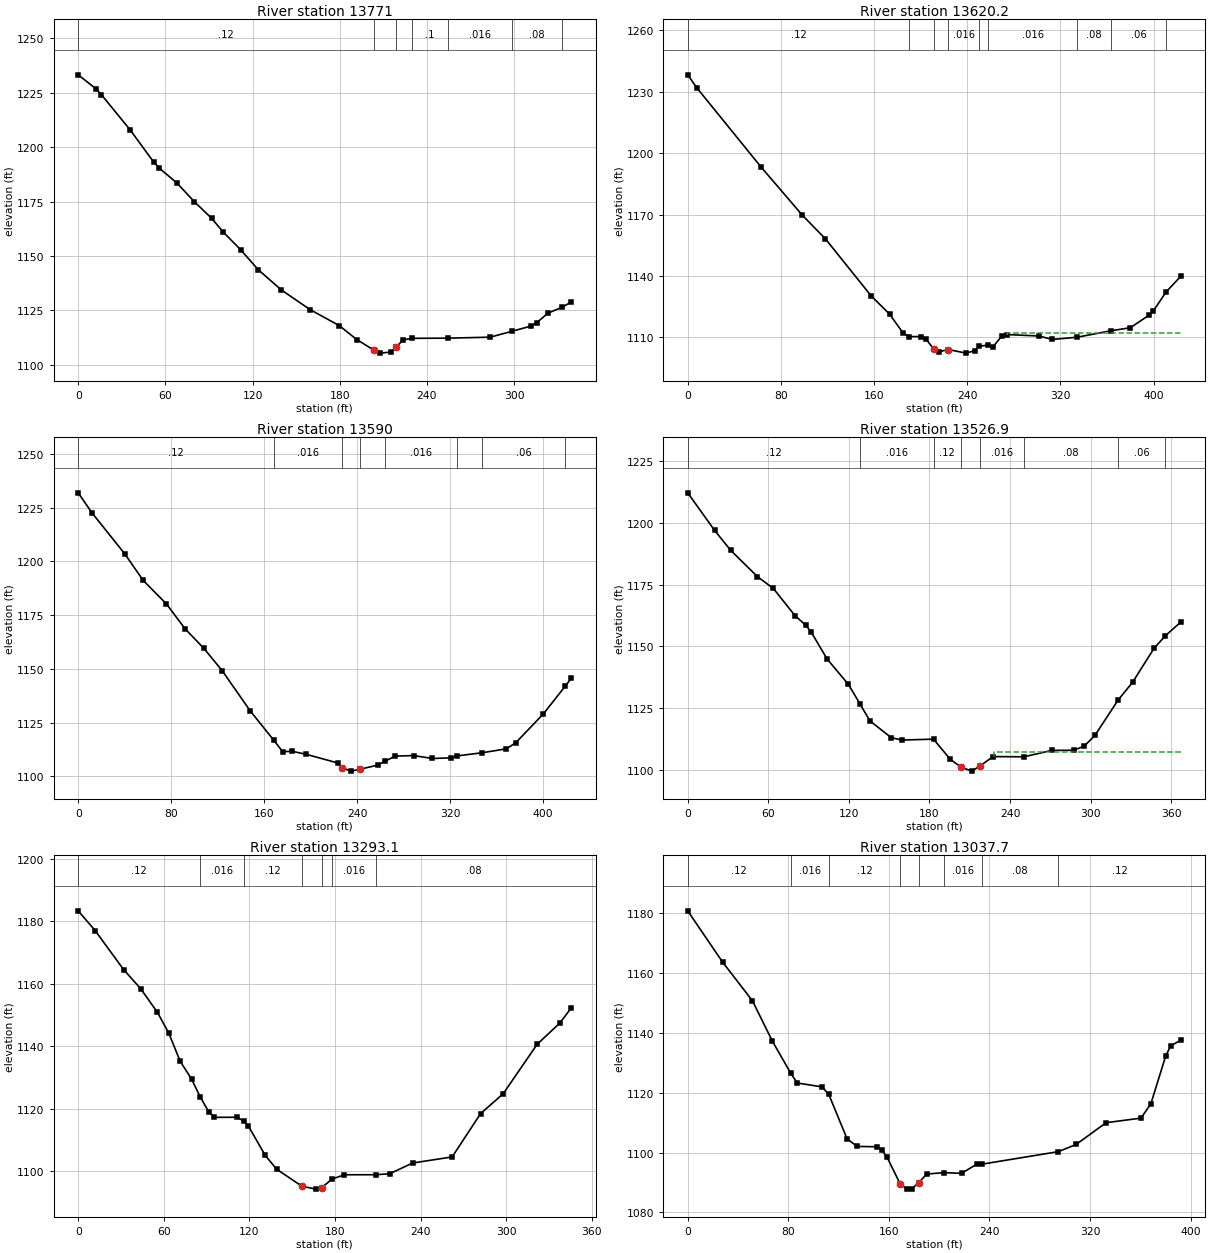
Type RM Length L Ch R = 1 ,13771   ,173,150.8,109.8
XS GIS Cut Line= 2
     1824460.605      363020.613     1824286.126      363311.759
#Sta/Elev= 30
       0 1233.23      12 1226.93      16  1224.1    35.9 1207.82    51.9  1193.2
    55.9 1190.29    67.9 1183.57    79.9 1174.98    91.8 1167.34    99.8    1161
   111.8 1152.88   123.8 1143.78   139.8  1134.4   159.7 1125.32   179.7 1118.01
   191.7 1111.62   203.8 1106.64   207.6 1105.36   215.6 1105.85   218.8 1108.02
   223.6 1111.47  229.641112.161  254.721112.241   283.5 1112.69  298.511115.372
   311.5 1117.77   315.5 1119.29   323.4 1123.74  332.95  1126.4   339.4 1128.84
#Mann= 7 ,-1 , 0
       0     .12       0   203.8    .045       0   218.8     .12       0
  229.64      .1       0  254.72    .016       0  298.51     .08       0
  332.95     .12       0
Bank Sta=203.8,218.8
XS Rating Curve= 0 ,0
Exp/Cntr=0.3,0.1

Type RM Length L Ch R = 1 ,13620.2 ,31.1,30.2,45.1
XS GIS Cut Line= 4
      1824354.72      362914.608      1824242.98      363072.004
     1824276.313      363132.421      1824173.47      363256.796
#Sta/Elev= 30
       0 1238.31     7.9 1231.91      63 1193.25    98.5 1169.67   118.2 1158.18
   157.6 1130.22   173.3 1121.38   185.2 1111.92  190.461110.347   200.7  1110.4
   204.5 1109.25  211.13 1104.39     216 1102.97   223.7 1104.05     239 1102.28
   246.7  1103.5  250.181105.597   258.11106.247     262 1105.25   269.9 1110.74
   273.8 1111.37   301.4 1110.66   313.2 1108.97  334.221110.043  363.711113.224
   380.1  1114.7   395.9 1120.73   399.8 1122.86  410.881132.226   423.4 1139.83
#Mann= 9 ,-1 , 0
       0     .12       0  190.46    .016       0  211.13    .045       0
   223.7    .016       0  250.18     .12       0   258.1    .016       0
  334.22     .08       0  363.71     .06       0  410.88     .12       0
#XS Ineff= 2 , 0
                          274.51          1112.3
Permanent Ineff=
       F       F
Bank Sta=211.13,223.7
XS Rating Curve= 0 ,0
Exp/Cntr=0.3,0.1

Type RM Length L Ch R = 1 ,13590   ,40.4,63.1,88.6
XS GIS Cut Line= 4
     1824329.355      362902.904     1824211.885      363069.675
     1824245.218      363130.092     1824149.147      363247.175
#Sta/Elev= 30
       0 1231.96      12 1222.55      40 1203.59      56 1191.15      76 1180.19
      92 1168.63     108 1159.64     124  1149.1     148 1130.46  168.151116.875
     176 1111.41     184 1111.62     196 1110.23   223.2 1106.18     227 1103.94
   234.7 1102.36   242.3 1103.19   257.7 1105.17  264.371107.066     273 1109.38
   288.9 1109.59   304.9 1108.25   320.8 1108.53  326.121109.438  347.971110.935
   368.6 1112.76   376.6 1115.56   400.5 1129.08  419.241141.948   424.4  1145.6
#Mann= 8 ,-1 , 0
       0     .12       0  168.15    .016       0     227    .045       0
   242.3     .12       0  264.37    .016       0  326.12     .08       0
  347.97     .06       0  419.24     .08       0
Bank Sta=227,242.3
XS Rating Curve= 0 ,0
Exp/Cntr=0.3,0.1

Type RM Length L Ch R = 1 ,13526.9 ,240.4,233.8,227.6
XS GIS Cut Line= 2
     1824280.917      362888.842      1824082.48      363197.696
#Sta/Elev= 30
       0 1212.12      20 1196.97    31.9 1188.94    51.9 1178.26    63.8 1173.45
    79.8 1162.51    87.8 1158.66    91.8 1155.95   103.8 1144.94   119.7 1134.65
  128.391126.661   135.7 1119.91   151.6 1113.13   159.6 1112.17  183.031112.538
   195.5 1104.37   203.5 1101.24   211.5 1099.61  217.63 1101.72   227.4 1105.48
  250.331105.404   271.3 1108.01   287.3 1108.03   295.3 1109.72   303.3 1114.14
  320.551128.423   331.2 1135.51   347.2 1149.26  355.661154.359   367.1 1159.86
#Mann= 8 ,-1 , 0
       0     .12       0  128.39    .016       0  183.03     .12       0
   203.5    .045       0  217.63    .016       0  250.33     .08       0
  320.55     .06       0  355.66     .08       0
#XS Ineff= 2 , 0
                          227.86          1107.2
Permanent Ineff=
       F       F
Bank Sta=203.5,217.63
XS Rating Curve= 0 ,0
Exp/Cntr=0.3,0.1

Type RM Length L Ch R = 1 ,13293.1 ,255.7,255.4,254.1
XS GIS Cut Line= 2
     1824033.326      362781.312       1823933.5      363112.258
#Sta/Elev= 30
       0 1183.39    11.9 1177.06    31.8  1164.6    43.7 1158.52    55.6 1150.86
    63.6 1144.15    71.5 1135.22    79.5 1129.53   85.491123.852    91.4 1119.14
    95.4 1117.27   111.2  1117.3  116.341116.074   119.2 1114.58   131.1 1105.11
   139.1 1100.68  156.89  1095.2   166.9 1094.29   170.8  1094.8  178.051097.529
   186.7 1098.89   208.91098.902   218.5 1099.23   234.4 1102.64   262.2  1104.6
   282.1 1118.46     298 1124.84   321.8 1140.68   337.7 1147.46   345.7 1152.33
#Mann= 7 ,-1 , 0
       0     .12       0   85.49    .016       0  116.34     .12       0
  156.89    .045       0   170.8     .12       0  178.05    .016       0
   208.9     .08       0
Bank Sta=156.89,170.8
XS Rating Curve= 0 ,0
Exp/Cntr=0.3,0.1

Type RM Length L Ch R = 1 ,13037.7 ,135.4,104.5,68.4
XS GIS Cut Line= 2
     1823788.209      362695.114     1823694.459      363075.843
#Sta/Elev= 30
       0 1180.73    27.7 1163.64    51.5 1150.68    67.3 1137.24   81.821126.584
    87.1 1123.23   106.9 1121.93  112.23  1119.4   126.7 1104.63   134.7 1102.05
   150.5 1101.94   154.5 1100.74   158.4 1098.56   168.9  1089.6   174.3 1087.79
   178.2 1087.93   183.9 1089.99   190.1 1092.83  203.49 1093.29   217.8 1093.07
   229.7 1096.07  233.911096.119  294.751100.302   308.9 1102.71   332.7 1109.97
   360.4  1111.5   368.3 1116.25   380.2 1132.36   384.2 1135.68   392.1  1137.5
#Mann= 8 ,-1 , 0
       0     .12       0   81.82    .016       0  112.23     .12       0
   168.9    .045       0   183.9     .12       0  203.49    .016       0
  233.91     .08       0  294.75     .12       0
Bank Sta=168.9,183.9
XS Rating Curve= 0 ,0
Exp/Cntr=0.3,0.1

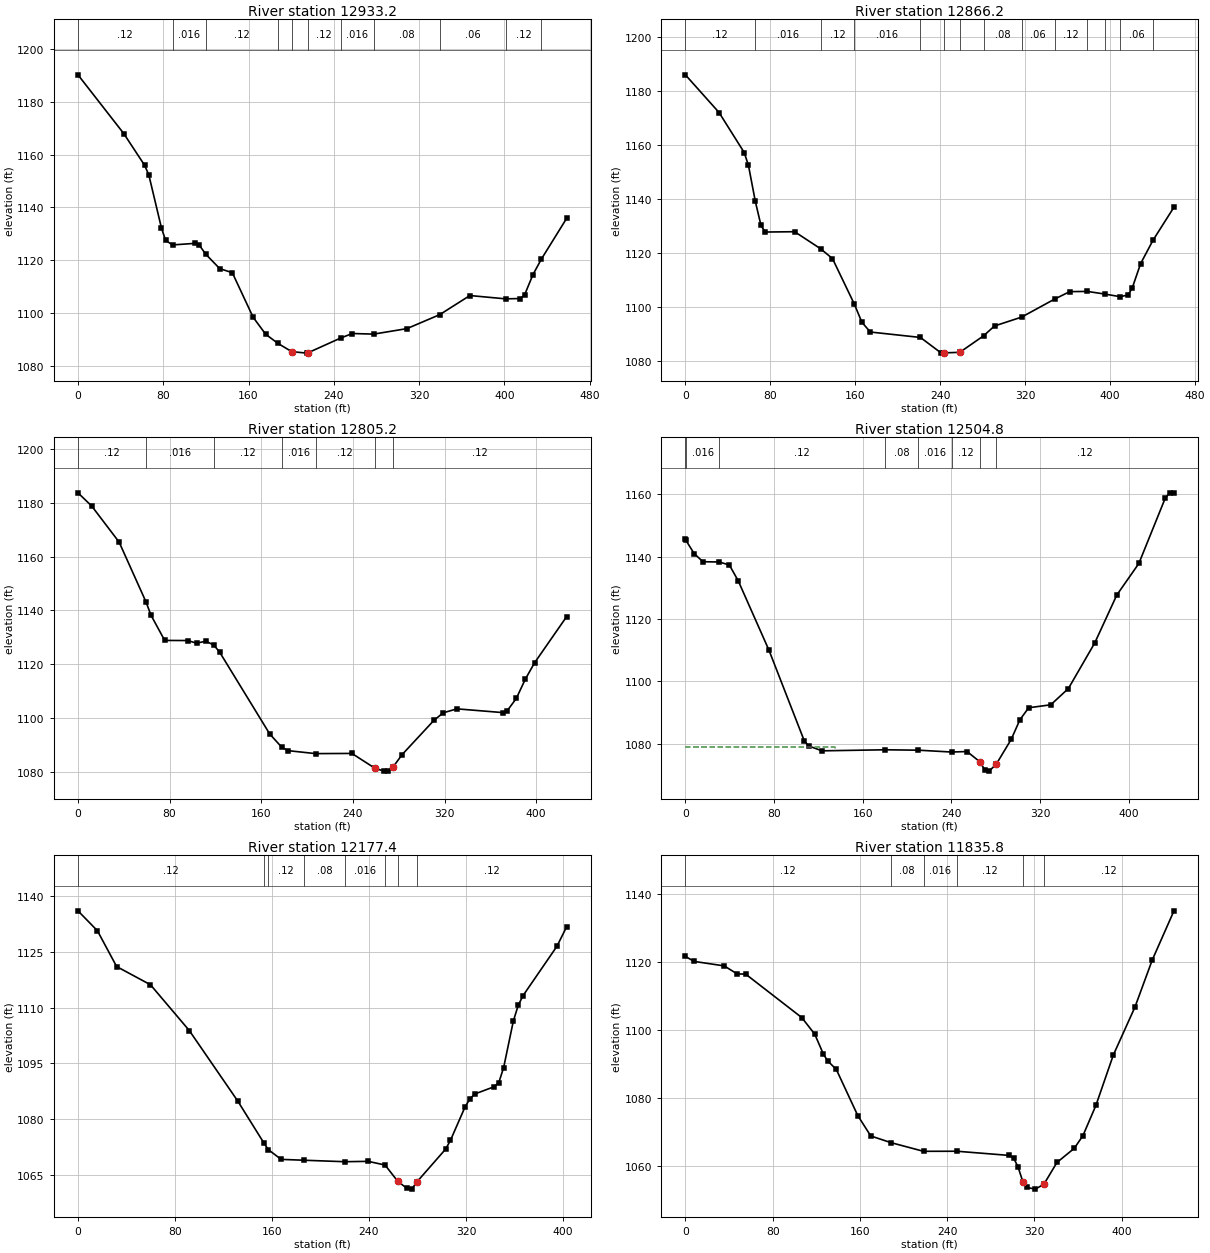
Type RM Length L Ch R = 1 ,12933.2 ,68.9,67,72.3
XS GIS Cut Line= 4
     1823672.063      362660.739     1823616.883       362827.95
     1823677.272      362862.301      1823613.73      363065.426
#Sta/Elev= 30
       0  1190.1      43  1167.9    62.6 1155.89    66.5 1152.25    78.3  1132.3
    82.2 1127.57   88.751125.861   109.6 1126.45   113.5 1125.96  119.861122.375
     133 1116.91   144.8 1115.38   164.3 1098.57   176.1 1092.13  187.571088.692
   200.5 1085.57   214.7    1085   215.5 1085.08  246.461090.696   257.4 1092.41
  277.411092.179   308.6 1094.25  339.311099.514   367.7 1106.75  401.211105.496
     415 1105.62     419 1106.97   426.9 1114.67  434.76  1120.5   458.4 1135.85
#Mann= 11 ,-1 , 0
       0     .12       0   88.75    .016       0  119.86     .12       0
  187.57    .016       0   200.5    .045       0   215.5     .12       0
  246.46    .016       0  277.41     .08       0  339.31     .06       0
  401.21     .12       0  434.76     .06       0
Bank Sta=200.5,215.5
XS Rating Curve= 0 ,0
Exp/Cntr=0.3,0.1

Type RM Length L Ch R = 1 ,12866.2 ,32.2,61,87.8
XS GIS Cut Line= 4
     1823631.095      362652.952     1823561.675      362863.454
     1823622.063      362897.805     1823572.068      363059.202
#Sta/Elev= 30
       0 1186.12    31.7 1172.14    55.4 1157.29    59.4 1152.51   65.851139.174
    71.2 1130.24    75.2 1127.79   102.9 1127.91  127.251121.602   138.5 1117.95
  159.151101.012   166.2 1094.31   174.2 1090.69  221.351088.675     241 1082.86
   243.4 1082.95   258.4 1083.16  280.821089.285   291.1 1092.93  316.71 1096.24
  347.631102.896   361.9 1105.67  378.551105.759  395.271104.758  409.481103.796
   416.9 1104.45   420.8 1107.03   428.7 1116.08   440.4 1124.77   460.1 1137.02
#Mann= 14 ,-1 , 0
       0     .12       0   65.85    .016       0  127.25     .12       0
  159.15    .016       0  221.35     .12       0   243.4    .045       0
   258.4     .12       0  280.82     .08       0  316.71     .06       0
  347.63     .12       0  378.55     .06       0  395.27     .12       0
  409.48     .06       0   440.4     .12       0
Bank Sta=243.4,258.4
XS Rating Curve= 0 ,0
Exp/Cntr=0.3,0.1

Type RM Length L Ch R = 1 ,12805.2 ,306,300.4,294.6
XS GIS Cut Line= 2
     1823550.188      362626.884     1823514.772      363051.884
#Sta/Elev= 30
       0 1183.71      12 1178.79    35.9  1165.4   59.271143.256    63.8 1138.16
    75.7 1128.82    95.7 1128.78   103.6  1127.8   111.6 1128.54  118.551127.102
   123.6 1124.51   167.4 1094.03  177.831089.125   183.3 1087.84  207.471086.733
   239.1  1086.8   259.1 1081.33     267 1080.22   270.8  1080.3     275 1081.73
     283 1086.39   310.9 1099.18   318.9 1101.91   330.8 1103.38   370.7 1101.99
   374.7 1102.68   382.6 1107.23   390.6 1114.49   398.6 1120.52   426.5 1137.63
#Mann= 7 ,-1 , 0
       0     .12       0   59.27    .016       0  118.55     .12       0
  177.83    .016       0  207.47     .12       0   259.1    .045       0
     275     .12       0
Bank Sta=259.1,275
XS Rating Curve= 0 ,0
Exp/Cntr=0.3,0.1

Type RM Length L Ch R = 1 ,12504.8 ,334.1,327.3,320.2
XS GIS Cut Line= 2
     1823185.019      362626.364     1823259.458      363060.978
#Sta/Elev= 30
       0 1145.57     .531145.253     7.9 1141.03    15.9 1138.41    30.51138.335
    39.7 1137.36    47.7 1132.28    75.5 1109.97   107.3 1080.94   111.2 1079.33
   123.2 1077.74  180.33 1078.08   210.31077.947  240.261077.355   254.2 1077.52
   265.6 1074.26   270.1 1071.73   274.1 1071.23   280.6 1073.49     294  1081.4
   301.9 1087.73   309.8 1091.56   329.7 1092.51   345.6 1097.72   369.4 1112.35
   389.3 1127.72   409.2 1137.85     433 1158.79     437 1160.52   440.9 1160.34
#Mann= 8 ,-1 , 0
       0     .12       0     .53    .016       0    30.5     .12       0
  180.33     .08       0   210.3    .016       0  240.26     .12       0
   265.6    .045       0   280.6     .12       0
#XS Ineff= 2 , 0
          134.67 1079.05
Permanent Ineff=
       F       F
Bank Sta=265.6,280.6
XS Rating Curve= 0 ,0
Exp/Cntr=0.3,0.1

Type RM Length L Ch R = 1 ,12177.4 ,336.9,341.6,346.3
XS GIS Cut Line= 2
     1822810.019      362786.086     1822995.783      363143.725
#Sta/Elev= 30
       0 1136.11      16 1130.76    31.9  1121.1    59.8  1116.2    91.8 1103.88
   131.7 1084.93  153.451073.531  156.961071.799   167.6 1069.17  186.731068.938
  220.011068.544   239.4 1068.64   253.31067.648   263.6 1063.34   271.3 1061.35
   275.3 1061.16   279.3 1063.01   303.2 1071.92   307.2 1074.27   319.2 1083.24
   323.2 1085.44   327.2 1086.77   343.2 1088.73   347.1 1089.84   351.1 1093.89
   359.1 1106.42   363.1 1110.64   367.1 1113.27     395 1126.53     403 1131.76
#Mann= 8 ,-1 , 0
       0     .12       0  153.45     .08       0  156.96     .12       0
  186.73     .08       0  220.01    .016       0   253.3     .12       0
   263.6    .045       0   279.3     .12       0
Bank Sta=263.6,279.3
XS Rating Curve= 0 ,0
Exp/Cntr=0.3,0.1

Type RM Length L Ch R = 1 ,11835.8 ,324,342.9,361.7
XS GIS Cut Line= 3
     1822584.325      362883.308     1822614.706      363098.586
     1822676.338      363320.808
#Sta/Elev= 30
       0  1121.7     7.9 1120.22    35.6  1118.9    47.4 1116.56    55.3 1116.48
   106.7 1103.73   118.6 1098.86   126.5 1093.03   130.4 1091.03   138.4 1088.49
   158.1 1074.93     170 1068.96  188.491067.002  218.341064.455  248.991064.475
   296.9 1063.25   300.9 1062.51   304.9 1059.97   309.4 1055.57   312.8 1053.88
   320.8 1053.35   328.7 1054.76   340.7 1061.18   356.6 1065.34   364.5 1069.04
   376.4 1077.91   392.4 1092.73   412.2 1106.79   428.1 1120.64     448 1135.07
#Mann= 6 ,-1 , 0
       0     .12       0  188.49     .08       0  218.34    .016       0
  248.99     .12       0   309.4    .045       0   328.7     .12       0
Bank Sta=309.4,328.7
XS Rating Curve= 0 ,0
Exp/Cntr=0.3,0.1

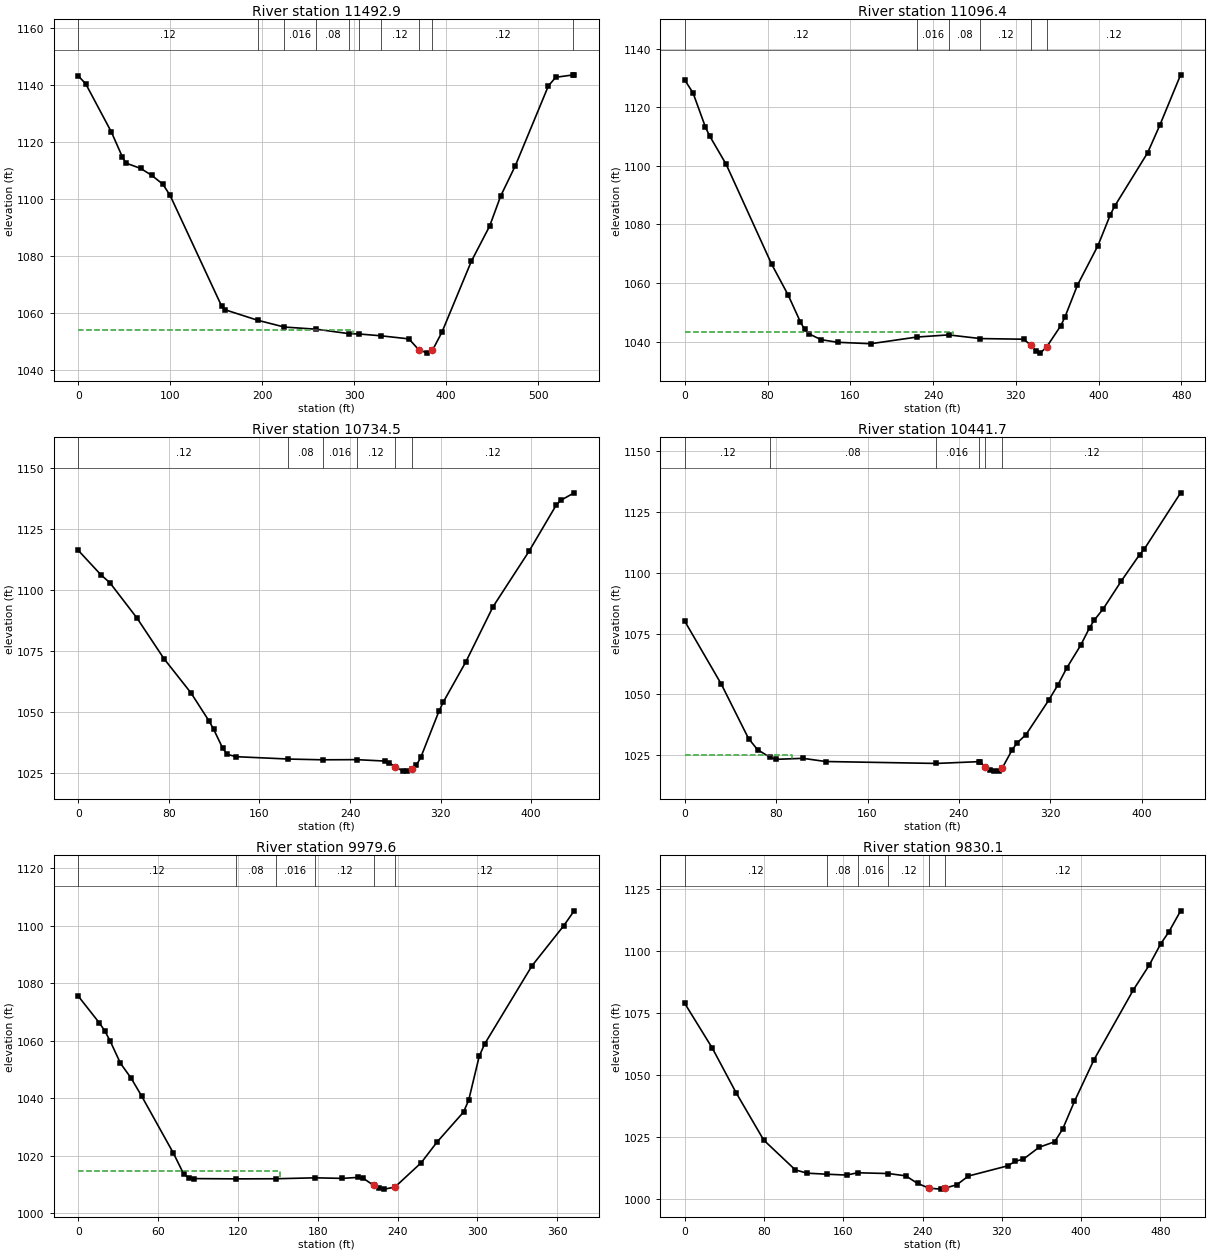
Type RM Length L Ch R = 1 ,11492.9 ,402.6,396.5,390
XS GIS Cut Line= 2
     1822514.012      362880.704     1822225.818      363336.433
#Sta/Elev= 30
       0  1143.3       8 1140.58      36  1123.6    47.9 1114.88    51.9 1112.73
    67.9 1110.84    79.9 1108.41    91.9 1105.33    99.8 1101.39   155.8 1062.54
   159.8 1061.22  195.011057.563  223.91 1055.18  258.861054.412  293.811052.879
  305.531052.732  328.761052.115   359.5 1051.02     370 1047.27   379.4 1046.02
     385 1046.96   395.4 1053.36   427.4 1078.27   447.3 1090.62   459.3 1101.18
   475.3 1111.86   511.2 1139.85   519.2 1142.86  538.441143.703   539.2 1143.72
#Mann= 10 ,-1 , 0
       0     .12       0  195.01     .08       0  223.91    .016       0
  258.86     .08       0  293.81     .12       0  305.53     .08       0
  328.76     .12       0     370    .045       0     385     .12       0
  538.44      .1       0
#XS Ineff= 2 , 0
          299.07 1054.19
Permanent Ineff=
       F       F
Bank Sta=370,385
XS Rating Curve= 0 ,0
Exp/Cntr=0.3,0.1

Type RM Length L Ch R = 1 ,11096.4 ,363.8,361.9,360.2
XS GIS Cut Line= 2
     1822053.943      362707.093     1821919.394      363167.162
#Sta/Elev= 30
       0 1129.26       8 1124.84      20 1113.14      24 1110.19      40 1100.49
    83.9 1066.44    99.9 1055.87   111.8 1046.64   115.8 1044.15   119.8 1042.67
   131.8 1040.62   147.8 1039.74   179.8 1039.25   224.21041.527  254.971042.265
  285.751041.008   327.6 1040.79   334.7  1038.7   339.5 1036.72   343.5 1036.04
   349.7 1038.11   363.5 1045.41   367.5 1048.39   379.5 1059.19   399.4 1072.76
   411.4 1083.33   415.4 1086.13   447.4 1104.44   459.4 1114.03   479.3 1131.05
#Mann= 6 ,-1 , 0
       0     .12       0   224.2    .016       0  254.97     .08       0
  285.75     .12       0   334.7    .045       0   349.7     .12       0
#XS Ineff= 2 , 0
          259.03 1043.11
Permanent Ineff=
       F       F
Bank Sta=334.7,349.7
XS Rating Curve= 0 ,0
Exp/Cntr=0.3,0.1

Type RM Length L Ch R = 1 ,10734.5 ,306.7,292.8,278.7
XS GIS Cut Line= 2
     1821669.394      362651.537     1821585.193      363081.225
#Sta/Elev= 30
       0 1116.06    19.9  1106.1    27.9  1102.8    51.8 1088.35    75.6 1071.73
    99.5 1057.67   115.4 1046.19   119.4 1042.87   127.4 1035.12   131.4 1032.52
   139.3 1031.55   185.6 1030.58   215.7 1030.27   245.81030.335   270.7 1029.75
   274.7 1029.06     280 1027.23   286.6 1025.73   290.6 1025.63     295 1026.46
   298.5 1028.02   302.5 1031.32   318.4 1050.08   322.4    1054   342.3 1070.46
   366.2 1092.96     398 1115.69   421.9 1134.52   425.9 1136.55   437.9 1139.67
#Mann= 6 ,-1 , 0
       0     .12       0   185.6     .08       0   215.7    .016       0
   245.8     .12       0     280    .045       0     295     .12       0
Bank Sta=280,295
XS Rating Curve= 0 ,0
Exp/Cntr=0.3,0.1

Type RM Length L Ch R = 1 ,10441.7 ,450.5,462.2,473.4
XS GIS Cut Line= 2
     1821227.554      362687.128     1821403.769      363083.829
#Sta/Elev= 30
       0 1080.06    31.9 1054.25    55.8 1031.83    63.7 1027.23   74.641024.112
    79.6 1023.27   103.5 1023.68   123.4 1022.37  220.161021.582  257.321022.315
   258.8 1022.11   263.1 1019.96   266.8 1018.72   270.8 1018.42   274.8 1018.52
   278.1 1019.84   286.7 1027.25   290.7  1029.9   298.7 1033.43   318.6 1047.58
   326.6 1053.84   334.5 1060.94   346.5 1070.11   354.4 1077.41   358.4 1080.47
   366.4 1085.22   382.3 1096.71   398.2 1107.48   402.2 1109.68   434.1 1132.89
#Mann= 6 ,-1 , 0
       0     .12       0   74.64     .08       0  220.16    .016       0
  257.32     .12       0   263.1    .045       0   278.1     .12       0
#XS Ineff= 2 , 0
           93.91 1025.07
Permanent Ineff=
       F       F
Bank Sta=263.1,278.1
XS Rating Curve= 0 ,0
Exp/Cntr=0.3,0.1

Type RM Length L Ch R = 1 ,9979.6  ,115.1,149.5,191.6
XS GIS Cut Line= 2
     1820924.429      362803.924     1820893.179      363175.452
#Sta/Elev= 30
       0 1075.45    15.9  1066.1    19.8 1063.46    23.8 1059.98    31.7  1052.1
    39.7 1046.94    47.6 1040.71    71.4 1020.92    79.3 1013.52    83.3 1012.24
    87.3    1012   118.81011.908  148.441011.951  178.081012.273   198.3 1012.08
   210.2 1012.41   214.2 1012.12   222.1 1009.62   226.1 1008.57     230 1008.34
     238 1009.04   257.8 1017.52   269.7 1024.72   289.6 1035.13   293.5 1039.28
   301.4 1054.53   305.4 1058.76   341.1 1086.04   364.9 1099.93   372.8 1105.15
#Mann= 6 ,-1 , 0
       0     .12       0   118.8     .08       0  148.44    .016       0
  178.08     .12       0   222.1    .045       0     238     .12       0
#XS Ineff= 2 , 0
           151.5  1014.8
Permanent Ineff=
       F       F
Bank Sta=222.1,238
XS Rating Curve= 0 ,0
Exp/Cntr=0.3,0.1

Type RM Length L Ch R = 1 ,9830.1  ,139.6,140,132
XS GIS Cut Line= 4
     1820868.873      362784.827     1820808.977      362983.134
     1820650.644      363033.829     1820690.054      363154.619
#Sta/Elev= 30
       0 1078.79    27.9 1060.74    51.8 1042.86    79.7  1023.8   111.6 1011.81
   123.5  1010.5  143.611010.079   163.3 1009.74  174.471010.664  205.321010.352
     223 1009.44   234.9 1006.39   246.7 1004.44   258.6 1004.08   262.6 1004.51
   274.4 1005.79   286.3 1009.35   325.9 1013.45   333.8 1015.33   341.7 1016.11
   357.6 1020.92   373.4 1023.15   381.4 1028.23   393.3 1039.37   413.1 1056.19
   452.8 1084.27   468.7 1094.15   480.6 1102.93   488.6 1107.57   500.5 1116.08
#Mann= 6 ,-1 , 0
       0     .12       0  143.61     .08       0  174.47    .016       0
  205.32     .12       0   246.7    .045       0   262.6     .12       0
Bank Sta=246.7,262.6
XS Rating Curve= 0 ,0
Exp/Cntr=0.3,0.1