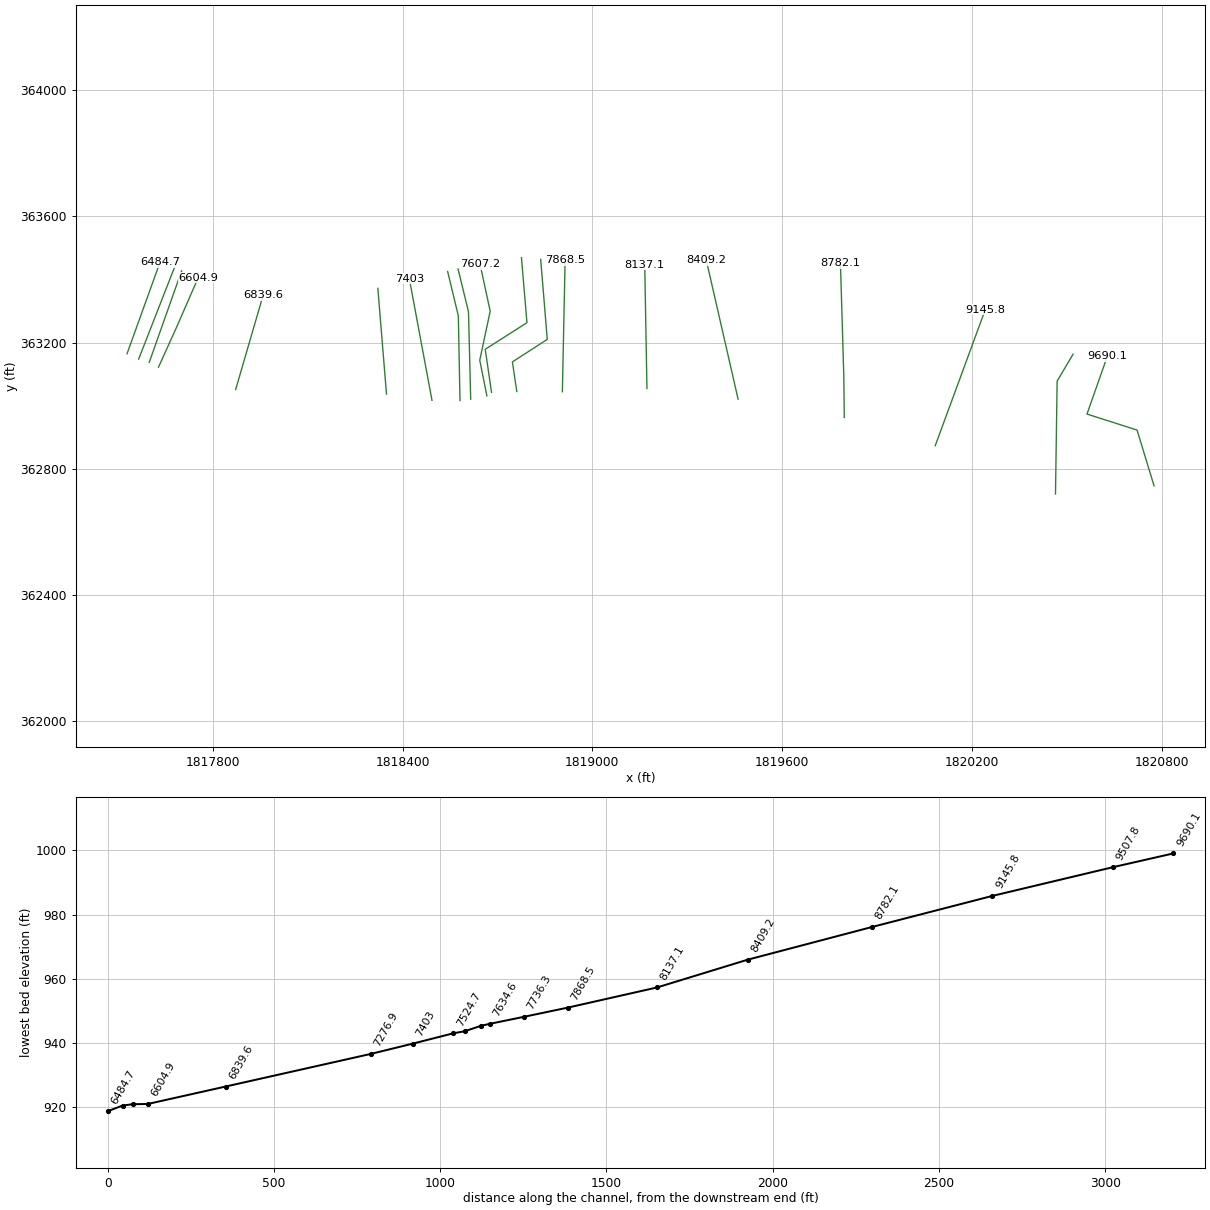
HEC-RAS study SENGCK.prj: SENGCK

--- SENGCK.g01 (geometry) --- (continued)

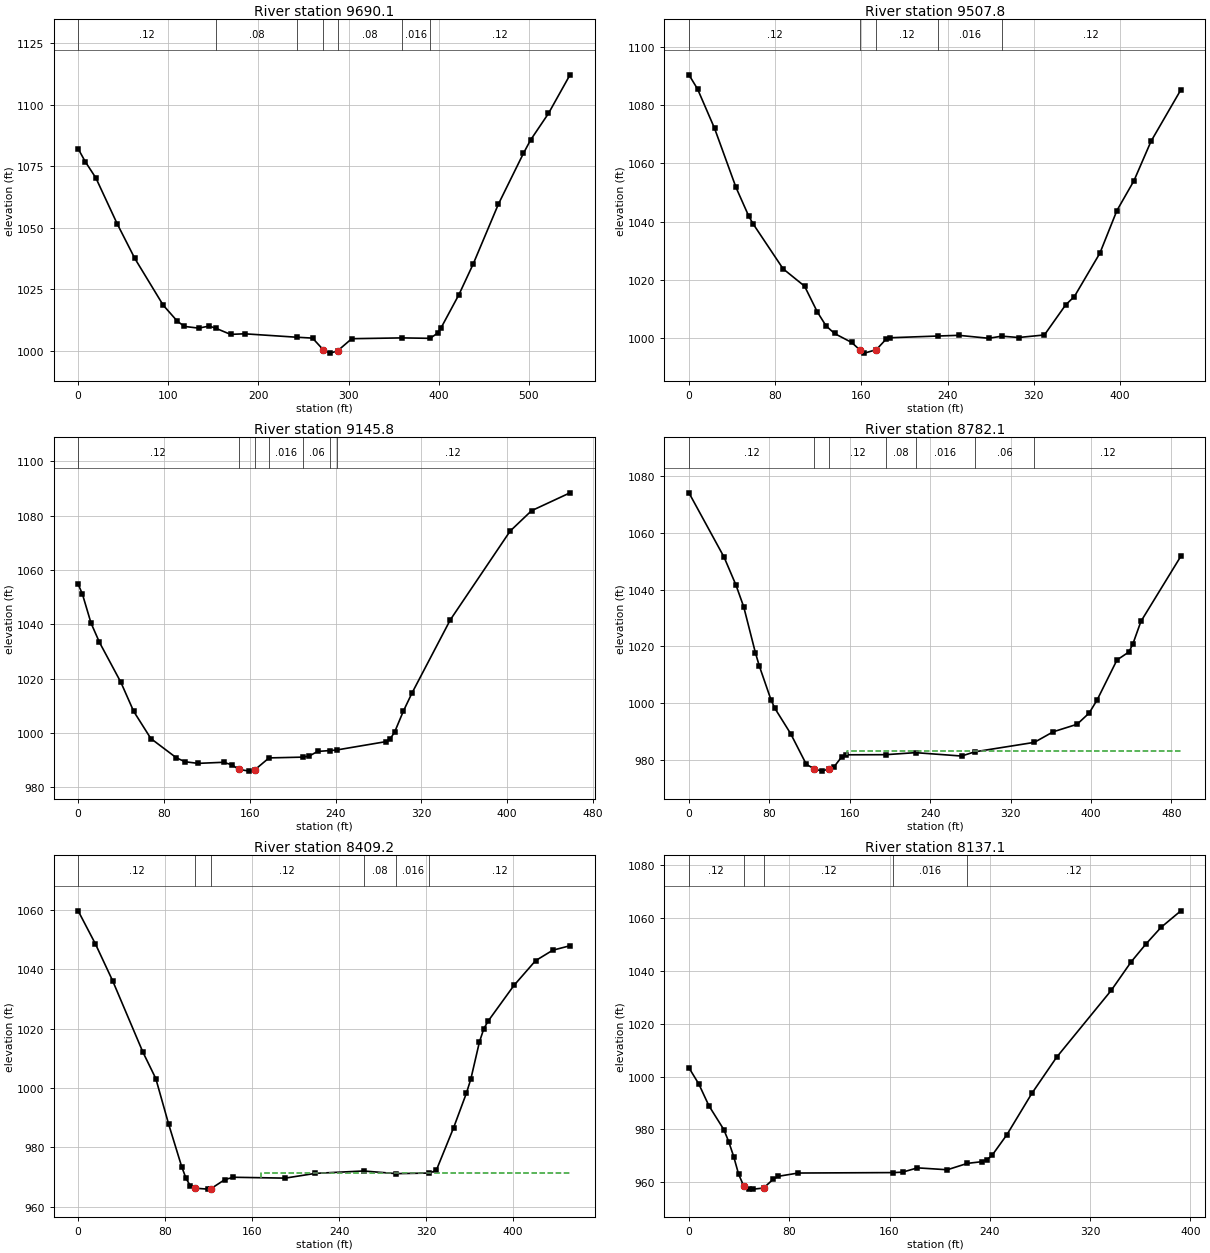
Type RM Length L Ch R = 1 ,9690.1  ,219,182.2,145
XS GIS Cut Line= 4
     1820775.991      362746.112     1820722.259      362922.978
     1820563.925      362973.673     1820628.422      363157.353
#Sta/Elev= 30
       0 1082.08     7.9 1076.82    19.7  1070.2    43.3 1051.62    62.9 1037.52
    94.4 1018.54   110.1 1012.03     118 1009.92   133.7 1009.23   145.5 1010.07
  153.281009.102   169.1 1006.69   184.8 1006.93  242.741005.529   260.1 1005.18
   271.9 1000.48   279.8  999.08   287.8  999.97   303.6 1004.94  359.271005.263
  390.581005.089   398.8 1007.19   402.8 1009.41   422.6 1022.88   438.5 1035.39
   466.3 1059.55   494.1  1080.2   502.1 1085.65   521.9 1096.41   545.8 1112.08
#Mann= 7 ,-1 , 0
       0     .12       0  153.28     .08       0  242.74     .12       0
   271.9    .045       0   287.8     .08       0  359.27    .016       0
  390.58     .12       0
Bank Sta=271.9,287.8
XS Rating Curve= 0 ,0
Exp/Cntr=0.3,0.1

Type RM Length L Ch R = 1 ,9507.8  ,369.5,362,354.4
XS GIS Cut Line= 3
     1820464.359      362720.591     1820469.568       363078.23
     1820519.915      363163.299
#Sta/Elev= 30
       0 1090.49       8 1085.61    23.8 1072.07    43.7 1051.75    55.6 1041.82
    59.6 1039.21    87.4 1023.78   107.3 1017.82   119.2 1008.92   127.2 1004.19
   135.1 1001.54     151  998.47   158.9  995.79   162.9  994.79   173.9  995.98
   182.8  999.52   186.8 1000.08  231.281000.676   250.4 1000.91   278.2   999.9
  290.36 1000.62     306 1000.16   329.9 1001.04   349.7 1011.42   357.7 1014.24
   381.4 1029.17   397.2 1043.83     413 1054.07   428.8  1067.6   456.5 1085.32
#Mann= 5 ,-1 , 0
       0     .12       0   158.9    .045       0   173.9     .12       0
  231.28    .016       0  290.36     .12       0
Bank Sta=158.9,173.9
XS Rating Curve= 0 ,0
Exp/Cntr=0.3,0.1

Type RM Length L Ch R = 1 ,9145.8  ,355.4,363.7,372.4
XS GIS Cut Line= 2
     1820084.151      362873.369     1820242.137      363303.924
#Sta/Elev= 30
       0 1054.79       4 1051.11      12 1040.45    19.9 1033.32    39.9 1018.56
    51.8 1007.89    67.8  997.87    91.7  990.74    99.7  989.32   111.7  988.72
   135.6  989.12   143.6  988.15   149.6  986.52   159.5  985.86   164.6   986.3
  177.99990.7344  209.46991.0188   215.4  991.42   223.3  993.12  234.73993.4415
  240.92993.6467   287.1  996.74   291.1  997.85   295.1 1000.28   303.1 1007.86
   311.1 1014.52     347 1041.64   402.8 1074.36   422.7 1081.85   458.6 1088.45
#Mann= 7 ,-1 , 0
       0     .12       0   149.6    .045       0   164.6     .12       0
  177.99    .016       0  209.46     .06       0  234.73     .08       0
  240.92     .12       0
Bank Sta=149.6,164.6
XS Rating Curve= 0 ,0
Exp/Cntr=0.3,0.1

Type RM Length L Ch R = 1 ,8782.1  ,367.9,372.9,377.8
XS GIS Cut Line= 3
     1819796.643      362962.781     1819795.029      363095.106
     1819784.476      363452.024
#Sta/Elev= 30
       0 1074.02      35 1051.36    46.7 1041.66    54.5 1033.93    66.2 1017.68
    70.1 1013.03    81.7 1001.16    85.6  998.17   101.2  989.32   116.8  978.52
   124.8  976.93   132.3  976.14   139.8  977.01   144.2  977.57   152.2  981.26
   156.1  981.88  195.88981.9244  225.43982.6385   271.2  981.45  284.53982.9379
  343.63986.2528   362.4  989.97   386.2  992.62   398.2  996.57   406.1 1001.16
   425.9 1015.24   437.8 1018.06   441.8 1020.97   449.7  1028.8   489.4  1051.7
#Mann= 7 ,-1 , 0
       0     .12       0   124.8    .045       0   139.8     .12       0
  195.88     .08       0  225.43    .016       0  284.53     .06       0
  343.63     .12       0
#XS Ineff= 2 , 0
                          156.86          983.31
Permanent Ineff=
       F       F
Bank Sta=124.8,139.8
XS Rating Curve= 0 ,0
Exp/Cntr=0.3,0.1

Type RM Length L Ch R = 1 ,8409.2  ,276.6,272,267
XS GIS Cut Line= 2
     1819460.887      363020.938     1819360.193      363461.911
#Sta/Elev= 30
       0 1059.59    15.9 1048.45    31.7 1036.09    59.5 1012.11    71.4 1003.19
    83.3  987.76    95.2  973.56    99.2  969.62   103.2  967.06   107.2  966.32
     119  965.99   122.2  966.16   134.9   969.2   142.8  969.98   190.4  969.69
   218.2  971.29  262.42 972.092  292.72971.1986  323.02 971.395   329.3  972.28
   345.2  986.59   357.1  998.34   361.1 1003.02     369 1015.49     373  1019.9
   376.9 1022.45   400.7 1034.48   420.6 1042.82   436.4 1046.34   452.3 1047.85
#Mann= 6 ,-1 , 0
       0     .12       0   107.2    .045       0   122.2     .12       0
  262.42     .08       0  292.72    .016       0  323.02     .12       0
#XS Ineff= 2 , 0
                          168.21          971.32
Permanent Ineff=
       F       F
Bank Sta=107.2,122.2
XS Rating Curve= 0 ,0
Exp/Cntr=0.3,0.1

Type RM Length L Ch R = 1 ,8137.1  ,269.2,268.6,267.5
XS GIS Cut Line= 2
     1819172.693      363054.619     1819165.748       363446.98
#Sta/Elev= 30
       0 1003.34     7.9  997.18    15.9  988.98    27.8  979.94    31.7  975.39
    35.7   969.7    39.6  963.06    43.6  958.65    47.6   957.5    51.5  957.36
    59.5  957.77    67.4  961.17    71.4  962.23    87.2  963.46  163.12963.6277
   170.4  963.79   182.3  965.42   206.1   964.7   222.2 967.127   233.9  967.77
   237.8  968.51   241.8  970.14   253.7  978.02   273.5   993.6   293.3 1007.33
   336.9 1032.68   352.8  1043.5   364.7 1050.32   376.6 1056.54   392.4 1062.82
#Mann= 5 ,-1 , 0
       0     .12       0    43.6    .045       0    59.5     .12       0
  163.12    .016       0   222.2     .12       0
#XS Ineff= 2 , 0
       0                     194       0
Permanent Ineff=
       F       F
Bank Sta=43.6,59.5
XS Rating Curve= 0 ,0
Exp/Cntr=0.3,0.1

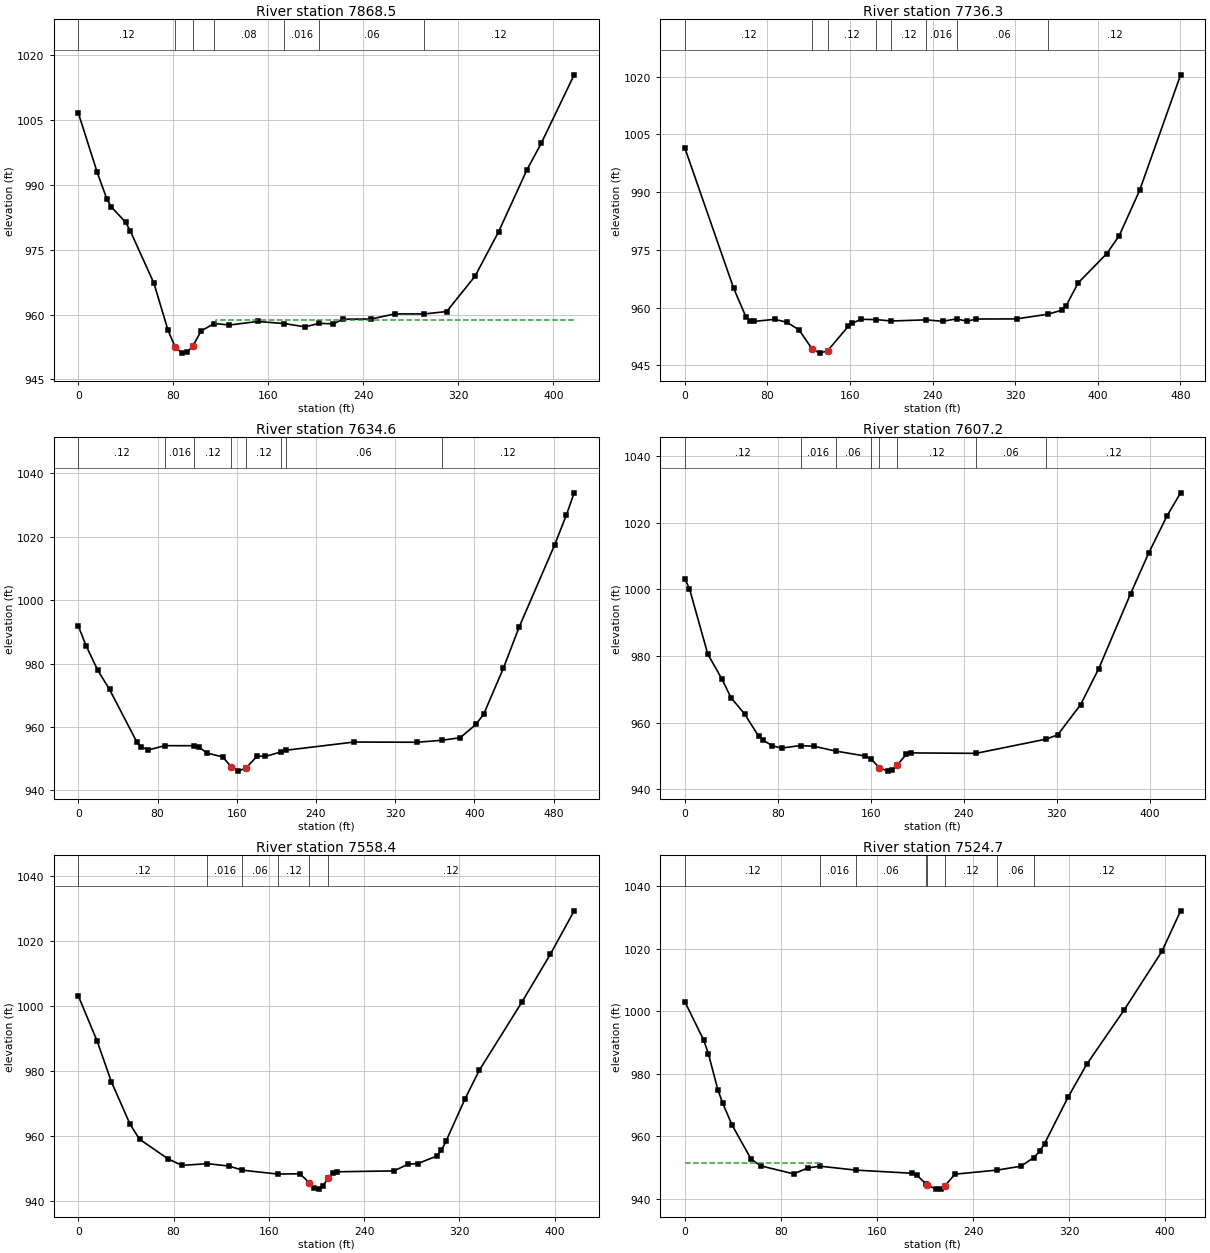
Type RM Length L Ch R = 1 ,7868.5  ,156.8,132.2,106.3
XS GIS Cut Line= 2
     1818905.331      363044.376     1818914.012      363461.911
#Sta/Elev= 30
       0 1006.61    15.9  992.89    23.9  986.82    27.8  984.89    39.8  981.36
    43.8  979.31    63.6  967.29    75.6  956.32    81.5  952.53    87.5  951.08
    91.5  951.24    96.5  952.75   103.4   956.2  114.29 957.926   127.3  957.58
   151.1   958.4  173.38957.9203   190.9  957.16  202.92957.9615   214.8  957.86
   222.7  958.92   246.6  958.97   266.5  960.15  291.55960.1472   310.2   960.7
   334.1  968.86     354  979.18   377.8  993.46   389.8  999.57   417.6 1015.45
#Mann= 7 ,-1 , 0
       0     .12       0    81.5    .045       0    96.5     .12       0
  114.29     .08       0  173.38    .016       0  202.92     .06       0
  291.55     .12       0
#XS Ineff= 2 , 0
                           116.1          958.75
Permanent Ineff=
       F       F
Bank Sta=81.5,96.5
XS Rating Curve= 0 ,0
Exp/Cntr=0.3,0.1

Type RM Length L Ch R = 1 ,7736.3  ,97.8,101.7,103.7
XS GIS Cut Line= 4
     1818761.234      363045.244     1818747.345      363138.994
     1818857.588      363210.174     1818836.755      363463.647
#Sta/Elev= 30
       0 1001.52    47.4     965    59.2  957.65    63.2  956.62    67.1  956.44
    86.9  956.99    98.8  956.25   110.7  954.24   123.3  949.31   130.6  948.21
   138.3  948.81   158.4   955.2   162.4  955.95   170.3  956.99  185.45956.9196
  200.14956.5551  233.57956.8521   249.8  956.49   263.2957.0982   273.7  956.48
   281.6  957.07   321.4   957.1  352.11958.3409   365.1  959.36   369.1  960.36
     381  966.43   408.8  974.08   420.7  978.65   440.6   990.5   480.3  1020.5
#Mann= 8 ,-1 , 0
       0     .12       0   123.3    .045       0   138.3     .12       0
  185.45     .08       0  200.14     .12       0  233.57    .016       0
   263.2     .06       0  352.11     .12       0
Bank Sta=123.3,138.3
XS Rating Curve= 0 ,0
Exp/Cntr=0.3,0.1

Type RM Length L Ch R = 1 ,7634.6  ,10.9,27.4,47.2
XS GIS Cut Line= 4
     1818681.373       363042.64     1818661.408      363178.924
     1818793.352      363263.126     1818775.991      363468.855
#Sta/Elev= 30
       0  991.84     7.9  985.56    19.7  977.84    31.5  971.83      59  955.28
      63  953.75    70.8  952.75    87.4954.0805  117.25954.0697     122  953.62
   129.9  951.76   145.6  950.54   154.3  947.48   161.2  946.05   169.3  947.01
   180.8  950.85   188.6  950.67  204.54952.0977  209.86952.6477   278.6  955.23
   341.9  955.16  367.26955.7861   385.6   956.6   401.5  960.78   409.4  964.06
   429.2  978.49   445.1  991.46   480.9 1017.36   492.8 1026.83   500.7 1033.86
#Mann= 8 ,-1 , 0
       0     .12       0    87.4    .016       0  117.25     .12       0
   154.3    .045       0   169.3     .12       0  204.54    .016       0
  209.86     .06       0  367.26     .12       0
#XS Ineff= 2 , 0
       0     110                       0
Permanent Ineff=
       F       F
Bank Sta=154.3,169.3
XS Rating Curve= 0 ,0
Exp/Cntr=0.3,0.1

Type RM Length L Ch R = 1 ,7607.2  ,42.9,48.8,53.7
XS GIS Cut Line= 4
      1818666.71      363031.423      1818644.14       363144.27
     1818677.127      363299.652     1818645.008      363448.957
#Sta/Elev= 30
       0 1003.16       4 1000.19    19.8  980.52    31.8  973.14    39.7   967.5
    51.6   962.5    63.5   955.9    67.5  954.66    75.4  953.02    83.3  952.34
   99.62953.0974   111.1  952.88  129.78951.4412   154.8  949.98  159.98949.1685
   167.4  946.44   174.6  945.42   178.6  945.82   182.4  947.13   190.5  950.42
   194.5  950.89  250.56950.7542  310.97955.0279   320.9  956.33   340.5  965.35
   356.2  976.21   383.6  998.71   399.2 1010.91   414.9 1022.03   426.6 1028.94
#Mann= 8 ,-1 , 0
       0     .12       0   99.62    .016       0  129.78     .06       0
  159.98     .12       0   167.4    .045       0   182.4     .12       0
  250.56     .06       0  310.97     .12       0
Bank Sta=167.4,182.4
XS Rating Curve= 0 ,0
Exp/Cntr=0.3,0.1

Type RM Length L Ch R = 1 ,7558.4  ,34.3,33.7,33.9
XS GIS Cut Line= 3
     1818615.495      363020.832      1818608.55      363297.742
     1818575.564      363433.159
#Sta/Elev= 30
       0 1003.06    15.8   989.2    27.7  976.73    43.5  963.61    51.4  959.05
    75.2  953.05    87.1     951  108.31951.5491   126.6   950.8  137.86949.5348
  167.41948.3569     186  948.43   193.9  945.72   197.8  944.09   201.8  943.72
   205.6  944.77   209.7  947.07   213.7   948.8   217.6  949.05   265.1  949.32
     277  951.38     285  951.56   300.9  953.86   304.9  955.59   308.8  958.46
   324.8   971.5   336.7  980.21   372.6 1001.23   396.5 1015.94   416.4 1029.22
#Mann= 6 ,-1 , 0
       0     .12       0  108.31    .016       0  137.86     .06       0
  167.41     .12       0   193.9    .045       0   209.7     .12       0
Bank Sta=193.9,209.7
XS Rating Curve= 0 ,0
Exp/Cntr=0.3,0.1

Type RM Length L Ch R = 1 ,7524.7  ,118.1,121.7,125.4
XS GIS Cut Line= 3
      1818581.64      363016.492     1818576.432      363284.721
     1818542.578      363425.346
#Sta/Elev= 30
       0 1003.07    15.8  990.72    19.7  986.32    27.6   974.8    31.6  970.54
    39.4  963.58    55.2  952.71    63.1  950.56    90.7  947.97   102.6   949.9
  112.64 950.438  142.19949.1886   189.4  948.17   193.3  947.56  201.27 944.601
   201.9  944.43   209.1   943.1     213  943.16   216.9  944.25   224.9  947.88
  260.35949.1979     280  950.44  290.51953.1589   295.6  955.22   299.6  957.68
   319.1  972.46   334.7  983.04     366 1000.48   397.3 1019.13   412.9 1032.12
#Mann= 8 ,-1 , 0
       0     .12       0  112.64    .016       0  142.19     .06       0
  201.27     .12       0   201.9    .045       0   216.9     .12       0
  260.35     .06       0  290.51     .12       0
#XS Ineff= 2 , 0
          114.04  951.32
Permanent Ineff=
       F       F
Bank Sta=201.9,216.9
XS Rating Curve= 0 ,0
Exp/Cntr=0.3,0.1

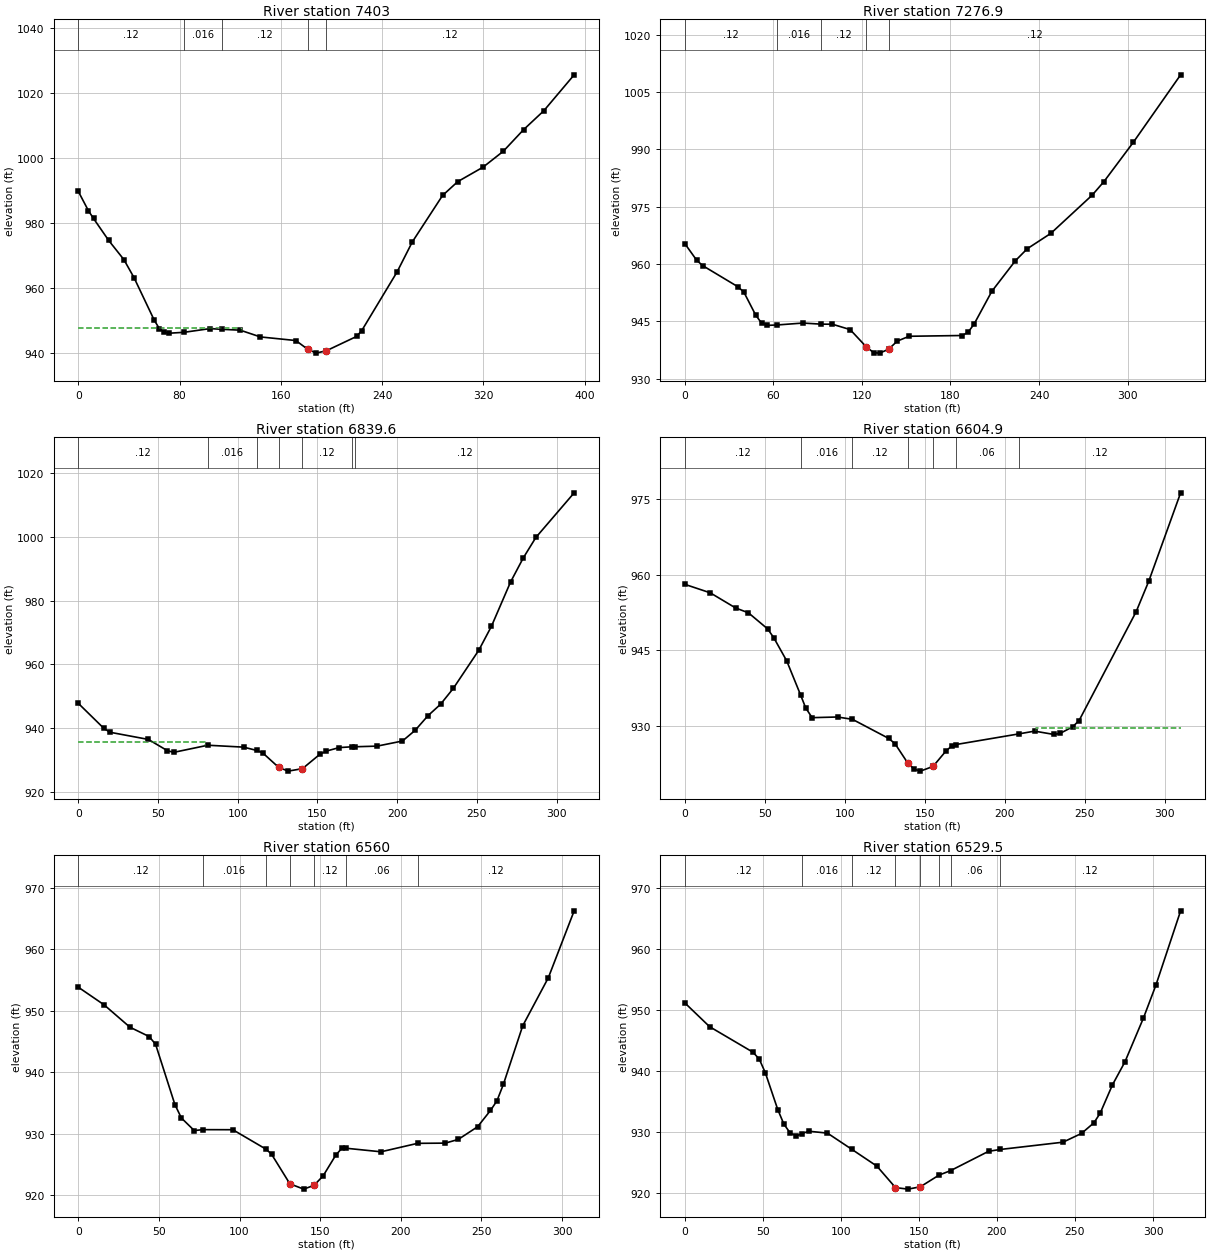
Type RM Length L Ch R = 1 ,7403    ,128.7,126.1,124
XS GIS Cut Line= 2
     1818493.073      363017.429     1818421.459      363402.628
#Sta/Elev= 30
       0  989.61       8  983.67      12   981.3      24  974.54      36  968.65
      44  963.11      60  950.01      64  947.45      68  946.28      72  946.02
   83.56946.2935     104  947.43   113.6 947.208   127.9  946.95   143.9  944.87
   171.9  943.76   181.1  941.11   187.9  939.89   196.1  940.64   219.9  945.03
   223.9  946.79   251.9  964.88   263.9  974.09   287.8  988.37   299.8  992.63
   319.8  997.08   335.8 1001.97   351.8  1008.6   367.8 1014.42   391.8 1025.48
#Mann= 5 ,-1 , 0
       0     .12       0   83.56    .016       0   113.6     .12       0
   181.1    .045       0   196.1     .12       0
#XS Ineff= 2 , 0
          129.62  947.77
Permanent Ineff=
       F       F
Bank Sta=181.1,196.1
XS Rating Curve= 0 ,0
Exp/Cntr=0.3,0.1

Type RM Length L Ch R = 1 ,7276.9  ,445.1,437.3,428.7
XS GIS Cut Line= 2
     1818349.247      363037.167     1818321.969      363371.996
#Sta/Elev= 30
       0  965.35       8  961.02      12  959.61      36  954.05      40  952.66
      48  946.66      52  944.54      56  943.95   62.62944.0586      80  944.56
   92.26944.2746     100  944.25     112  942.85     123  938.31     128   936.8
     132  936.69     138   937.7     144  939.85     152   941.1     188   941.3
     192   942.2     196   944.3     208  952.86     224  960.88     232     964
     248  968.03     276  978.03     284  981.59   303.9  991.87   335.9  1009.5
#Mann= 5 ,-1 , 0
       0     .12       0   62.62    .016       0   92.26     .12       0
     123    .045       0     138     .12       0
Bank Sta=123,138
XS Rating Curve= 0 ,0
Exp/Cntr=0.3,0.1

Type RM Length L Ch R = 1 ,6839.6  ,237.8,234.7,231.8
XS GIS Cut Line= 2
     1817872.345      363051.147     1817959.151      363349.758
#Sta/Elev= 30
       0  947.76      16  939.93    19.9   938.7    43.9  936.46    55.8  932.95
    59.8   932.4   81.21934.6387   103.7  934.04  111.97932.9951   115.6  932.26
   125.6  927.72   131.6  926.52   140.6   927.3   151.5   931.8   155.5  932.79
   163.5  933.89  171.56934.1505  173.49934.1552   187.4  934.36   203.3  935.96
   211.3  939.33   219.3  943.89   227.2  947.48   235.2  952.46   251.2  964.43
   259.1  971.91   271.1   985.8   279.1  993.37     287  999.78     311 1013.76
#Mann= 7 ,-1 , 0
       0     .12       0   81.21    .016       0  111.97     .12       0
   125.6    .045       0   140.6     .12       0  171.56     .06       0
  173.49     .12       0
#XS Ineff= 2 , 0
           79.46  935.54
Permanent Ineff=
       F       F
Bank Sta=125.6,140.6
XS Rating Curve= 0 ,0
Exp/Cntr=0.3,0.1

Type RM Length L Ch R = 1 ,6604.9  ,43,44.9,46.5
XS GIS Cut Line= 3
     1817628.462      363122.216     1817685.808      363249.195
     1817753.943      363405.661
#Sta/Elev= 30
       0  958.11    15.9  956.43    31.8  953.42    39.8  952.46    51.8  949.27
    55.7  947.49    63.7  942.95   72.41 936.168    75.6   933.6    79.6  931.68
    95.5  931.81  104.82931.3482   127.4  927.58   131.4  926.53   139.3  922.73
   143.3  921.48   147.3  921.08   155.2  922.01   163.1     925   167.1  926.14
  169.46926.3465  208.64928.4498   218.7  929.01   230.6  928.36   234.6  928.55
   242.5  929.87   246.5   931.1   282.2  952.69   290.1  958.75     310  976.25
#Mann= 7 ,-1 , 0
       0     .12       0   72.41    .016       0  104.82     .12       0
   139.3    .045       0   155.2     .12       0  169.46     .06       0
  208.64     .12       0
#XS Ineff= 2 , 0
                          219.61          929.63
Permanent Ineff=
       F       F
Bank Sta=139.3,155.2
XS Rating Curve= 0 ,0
Exp/Cntr=0.3,0.1

Type RM Length L Ch R = 1 ,6560    ,31.2,30.5,29.7
XS GIS Cut Line= 2
     1817599.175      363137.499     1817701.606       363427.43
#Sta/Elev= 30
       0  953.85      16  950.98      32  947.35    43.9  945.83    47.9  944.58
    59.9  934.76    63.9  932.59    71.9  930.54   77.14930.6906    95.8  930.68
  116.43927.5104   119.8  926.71   131.2  921.88   139.8  921.02   146.2  921.64
   151.8  923.17   159.7  926.56   163.7  927.75  165.81927.6761   187.7  927.09
  210.41928.4651   227.6   928.5   235.6   929.1   247.6  931.16   255.6  933.81
   259.6  935.37   263.6  938.05   275.6  947.58   291.5   955.4   307.5  966.27
#Mann= 7 ,-1 , 0
       0     .12       0   77.14    .016       0  116.43     .12       0
   131.2    .045       0   146.2     .12       0  165.81     .06       0
  210.41     .12       0
#XS Ineff= 2 , 0
       0                   163.7       0
Permanent Ineff=
       F       F
Bank Sta=131.2,146.2
XS Rating Curve= 0 ,0
Exp/Cntr=0.3,0.1

Type RM Length L Ch R = 1 ,6529.5  ,44,44.8,45.3
XS GIS Cut Line= 2
     1817565.668      363147.742      1817681.12      363443.749
#Sta/Elev= 30
       0  951.15    15.9  947.24    43.7  943.05    47.7  941.93    51.6  939.68
    59.6  933.62    63.5  931.25    67.5  929.81    71.5  929.32   75.14929.7022
    79.4  930.09    91.4  929.78  106.84927.1494   123.1  924.36     135  920.84
     143  920.59   150.9  920.97  162.93922.8953  170.25923.6174   194.6  926.79
  201.95927.0919   242.3  928.29   254.2  929.73   262.1  931.46   266.1  933.02
     274  937.69     282  941.46   293.9  948.68   301.8  954.01   317.7  966.25
#Mann= 8 ,-1 , 0
       0     .12       0   75.14    .016       0  106.84     .12       0
     135    .045       0   150.9     .06       0  162.93     .12       0
  170.25     .06       0  201.95     .12       0
Bank Sta=135,150.9
XS Rating Curve= 0 ,0
Exp/Cntr=0.3,0.1

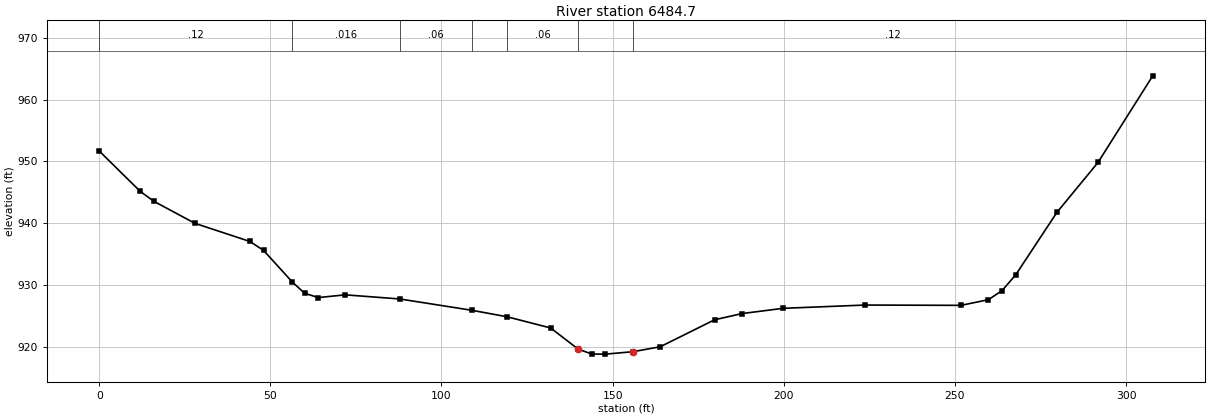
Type RM Length L Ch R = 1 ,6484.7  ,118.3,118.8,119.1
XS GIS Cut Line= 2
     1817528.943      363164.688     1817633.109      363454.272
#Sta/Elev= 30
       0  951.69      12  945.15      16  943.54      28  939.98      44  937.06
      48  935.62   56.39930.5121      60  928.68      64  927.98    71.9  928.42
   87.78927.7548  108.89 925.921  119.17924.8721   131.9  923.06   139.9  919.65
   143.9  918.84   147.9  918.83   155.9  919.22   163.9  920.02   179.8  924.39
   187.8  925.39   199.8  926.24   223.8  926.77   251.8  926.72   259.8  927.64
   263.8  929.12   267.8  931.68   279.8  941.76   291.8  949.83   307.8  963.85
#Mann= 7 ,-1 , 0
       0     .12       0   56.39    .016       0   87.78     .06       0
  108.89     .12       0  119.17     .06       0   139.9    .045       0
   155.9     .12       0
Bank Sta=139.9,155.9
XS Rating Curve= 0 ,0
Exp/Cntr=0.3,0.1