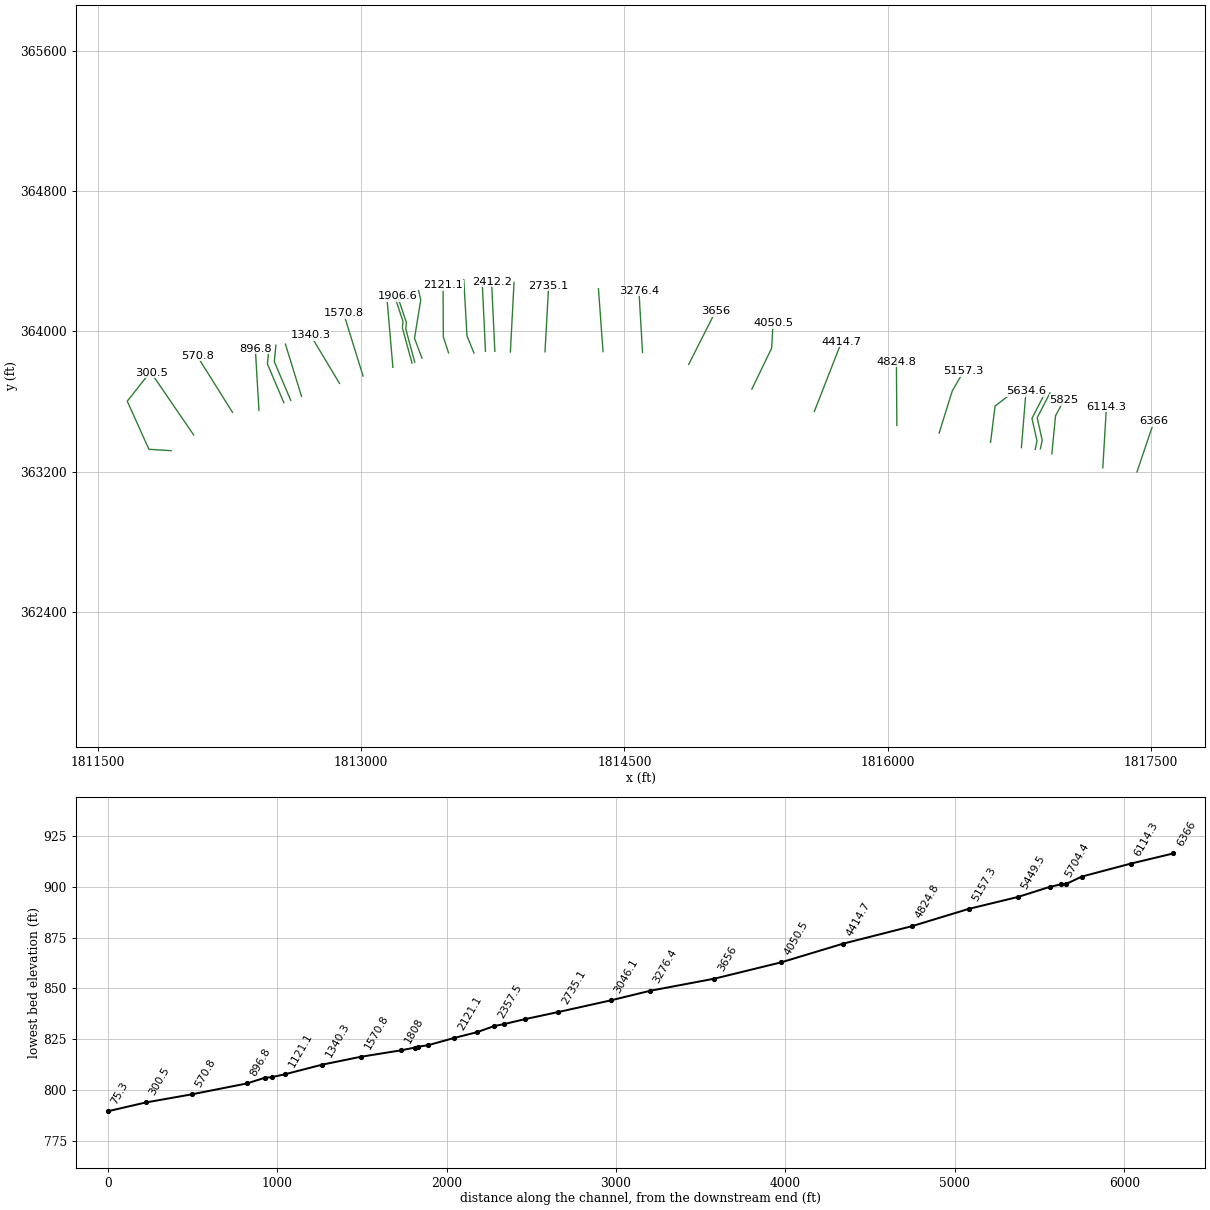
HEC-RAS study SENGCK.prj: SENGCK

--- SENGCK.g01 (geometry) --- (continued)

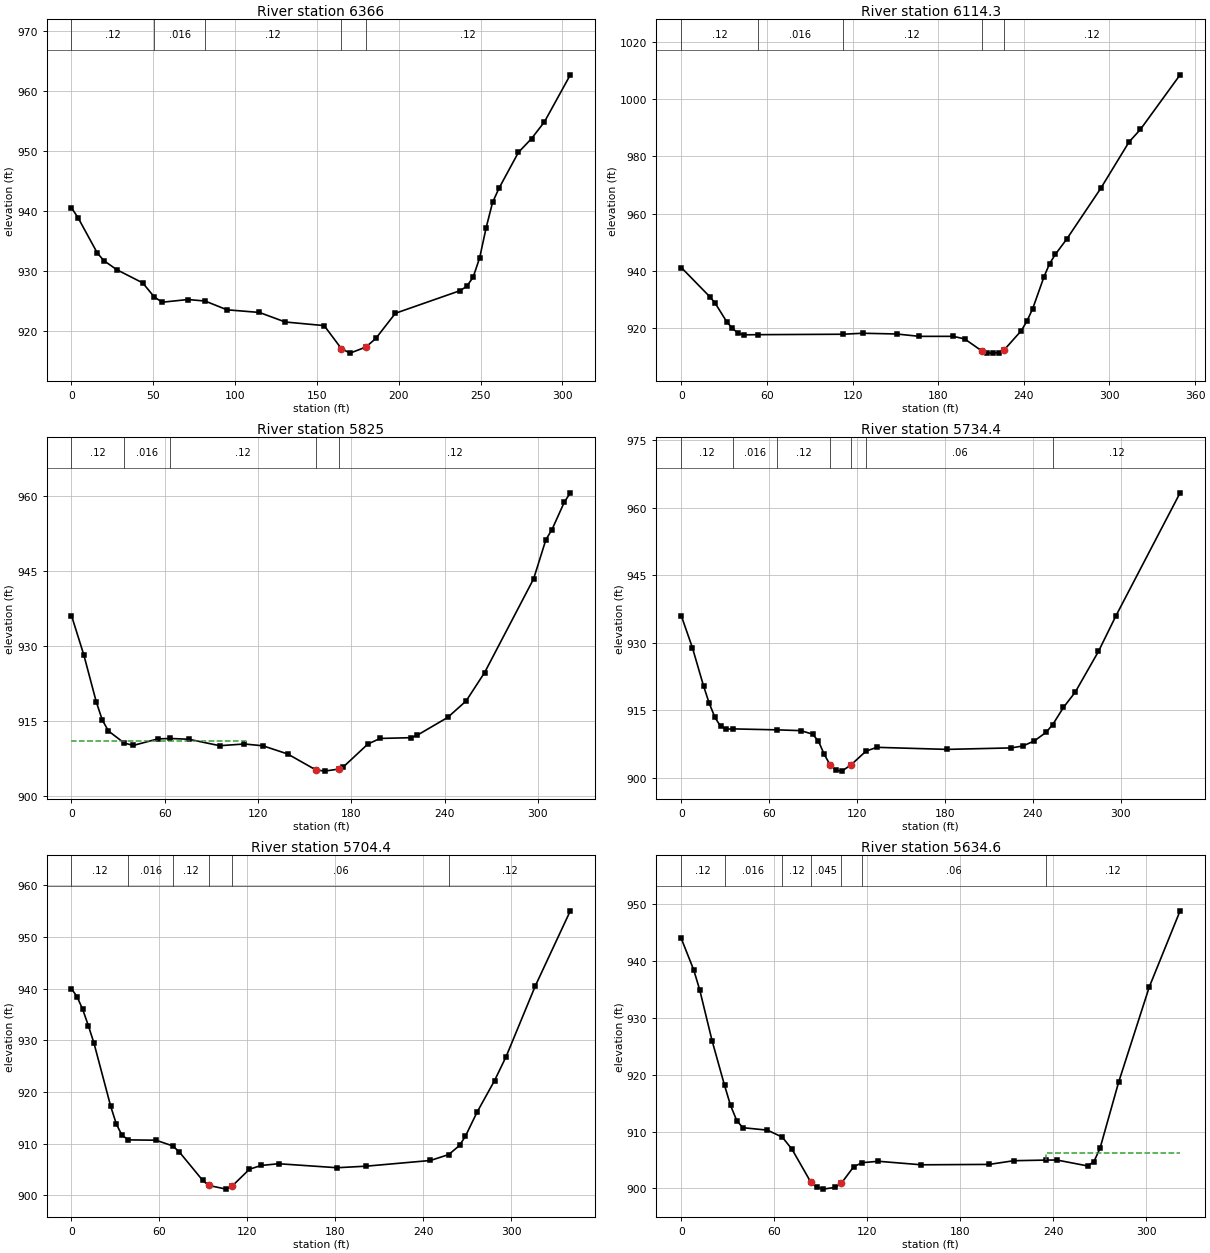
Type RM Length L Ch R = 1 ,6366    ,245.8,251.7,257.8
XS GIS Cut Line= 2
     1817421.998      363199.411      1817519.22      363488.299
#Sta/Elev= 30
       0  940.54       4   938.9    15.8  933.01    19.8  931.75    27.7  930.24
    43.5  928.05   50.52925.7279    55.4  924.83    71.2  925.28   81.68925.0256
      95  923.57   114.8  923.13   130.6  921.54   154.4  920.94   164.9  917.11
   170.2  916.36   179.9  917.37     186  918.82   197.9  922.99   237.5  926.76
   241.5  927.48   245.4  928.98   249.4  932.22   253.4  937.26   257.3  941.45
   261.3  943.84   273.1  949.77   281.1  952.06     289  954.85   304.8  962.67
#Mann= 5 ,-1 , 0
       0     .12       0   50.52    .016       0   81.68     .12       0
   164.9    .045       0   179.9     .12       0
Bank Sta=164.9,179.9
XS Rating Curve= 0 ,0
Exp/Cntr=0.3,0.1

Type RM Length L Ch R = 1 ,6114.3  ,290.2,289.3,288.5
XS GIS Cut Line= 2
     1817227.054      363223.031     1817247.808      363571.896
#Sta/Elev= 30
       0  941.23    19.9  931.08    23.8  928.74    31.8  922.34    35.7  920.04
    39.7  918.34    43.7  917.73   53.89917.7915  113.07917.9393   127.1  918.29
   150.9  918.03   166.8   917.2   190.6  917.21   198.6  916.29   210.5  912.14
   214.5   911.4   218.4  911.35   222.4  911.56   226.4  912.57   238.3  919.22
   242.3  922.65   246.2  926.83   254.2  938.06   258.1   942.6   262.1  945.82
     270   951.1   293.9  968.84   313.7  985.02   321.7  989.42   349.5 1008.47
#Mann= 5 ,-1 , 0
       0     .12       0   53.89    .016       0  113.07     .12       0
   210.5    .045       0   226.4     .12       0
#XS Ineff= 2 , 0
       0     183                       0
Permanent Ineff=
       F       F
Bank Sta=210.5,226.4
XS Rating Curve= 0 ,0
Exp/Cntr=0.3,0.1

Type RM Length L Ch R = 1 ,5825    ,82.9,90.5,97.6
XS GIS Cut Line= 3
     1816936.581      363302.188     1816957.613      363519.556
     1817006.441      363609.616
#Sta/Elev= 30
       0  936.05     7.9  928.22    15.9  918.85    19.8  915.18    23.8  912.98
   33.88  910.59    39.7   910.1    55.6  911.41   63.55 911.489    75.4  911.34
    95.3  910.05   111.2  910.39   123.1  910.03     139   908.4     157  905.24
   162.8  904.97     172  905.39   174.7  905.77   190.6  910.38   198.5   911.5
   218.4  911.65   222.3  912.13     242  915.71   253.8  918.99   265.7  924.67
   297.2  943.38   305.1  951.21     309  953.22   316.9  958.67   320.8  960.56
#Mann= 5 ,-1 , 0
       0     .12       0   33.88    .016       0   63.55     .12       0
     157    .045       0     172     .12       0
#XS Ineff= 2 , 0
          111.97     911
Permanent Ineff=
       F       F
Bank Sta=157,172
XS Rating Curve= 0 ,0
Exp/Cntr=0.3,0.1

Type RM Length L Ch R = 1 ,5734.4  ,30.2,30,30.2
XS GIS Cut Line= 4
     1816871.224      363330.902      1816881.64      363379.513
     1816852.995      363507.985     1816925.911      363649.478
#Sta/Elev= 30
       0  935.97     7.6  928.86    15.3  920.26    19.1  916.49      23  913.35
    26.8   911.4    30.6  910.75   35.33910.8071   65.56910.5907    81.6  910.42
    89.6  909.64    93.6  908.11    97.6  905.14   101.6  902.82   105.6  901.59
   109.6  901.42  115.74  902.77  126.09905.8621   133.5  906.71   181.3  906.25
   225.1  906.58   233.1     907     241  908.13     249  910.04  253.58911.7742
   260.9  915.59   268.9  918.96   284.8  928.04   296.7  935.93   340.5  963.27
#Mann= 7 ,-1 , 0
       0     .12       0   35.33    .016       0   65.56     .12       0
   101.6    .045       0  115.74     .12       0  126.09     .06       0
  253.58     .12       0
Bank Sta=101.6,115.74
XS Rating Curve= 0 ,0
Exp/Cntr=0.3,0.1

Type RM Length L Ch R = 1 ,5704.4  ,76.7,69.8,63
XS GIS Cut Line= 4
     1816841.536       363327.43     1816851.953      363376.041
     1816823.307      363504.513     1816896.224      363646.006
#Sta/Elev= 30
       0  939.97     3.8  938.41     7.6  936.01    11.5  932.83    15.3  929.49
    26.8  917.19    30.6  913.81    34.4  911.64   38.88910.7274    57.7  910.66
   69.12909.5572    73.6  908.39    89.6  902.88    93.6  901.92   105.6   901.2
   109.6  901.78   121.5  905.05   129.5  905.78   141.4  906.11   181.3  905.34
   201.2  905.64     245  906.74  257.49907.8842   264.9  909.65   268.9  911.44
   276.8  916.06   288.8   922.2   296.7  926.85   316.6   940.5   340.5  955.03
#Mann= 6 ,-1 , 0
       0     .12       0   38.88    .016       0   69.12     .12       0
    93.6    .045       0   109.6     .06       0  257.49     .12       0
Bank Sta=93.6,109.6
XS Rating Curve= 0 ,0
Exp/Cntr=0.3,0.1

Type RM Length L Ch R = 1 ,5634.6  ,184.7,185.1,191.7
XS GIS Cut Line= 2
      1816762.97      363337.605     1816789.359      363658.438
#Sta/Elev= 30
       0  943.99       8  938.48    11.9  934.95    19.9  925.98   27.94918.1323
    31.8  914.61    35.8  911.95    39.7  910.69    55.6  910.26   65.22909.0274
    71.5  906.88    83.5  901.15    87.4  900.21    91.4  899.88    99.4  900.19
   103.3  900.91   111.3  903.84  116.85904.5377   127.2  904.78     155  904.16
   198.7  904.23   214.6  904.88  235.39  904.99   242.4     905   262.3  903.96
   266.3  904.73   270.2  907.04   282.2  918.66     302  935.45   321.9  948.85
#Mann= 7 ,-1 , 0
       0     .12       0   27.94    .016       0   65.22     .12       0
    83.5    .045       0   103.3     .12       0  116.85     .06       0
  235.39     .12       0
#XS Ineff= 2 , 0
                           235.5          906.22
Permanent Ineff=
       F       F
Bank Sta=83.5,103.3
XS Rating Curve= 0 ,0
Exp/Cntr=0.3,0.1

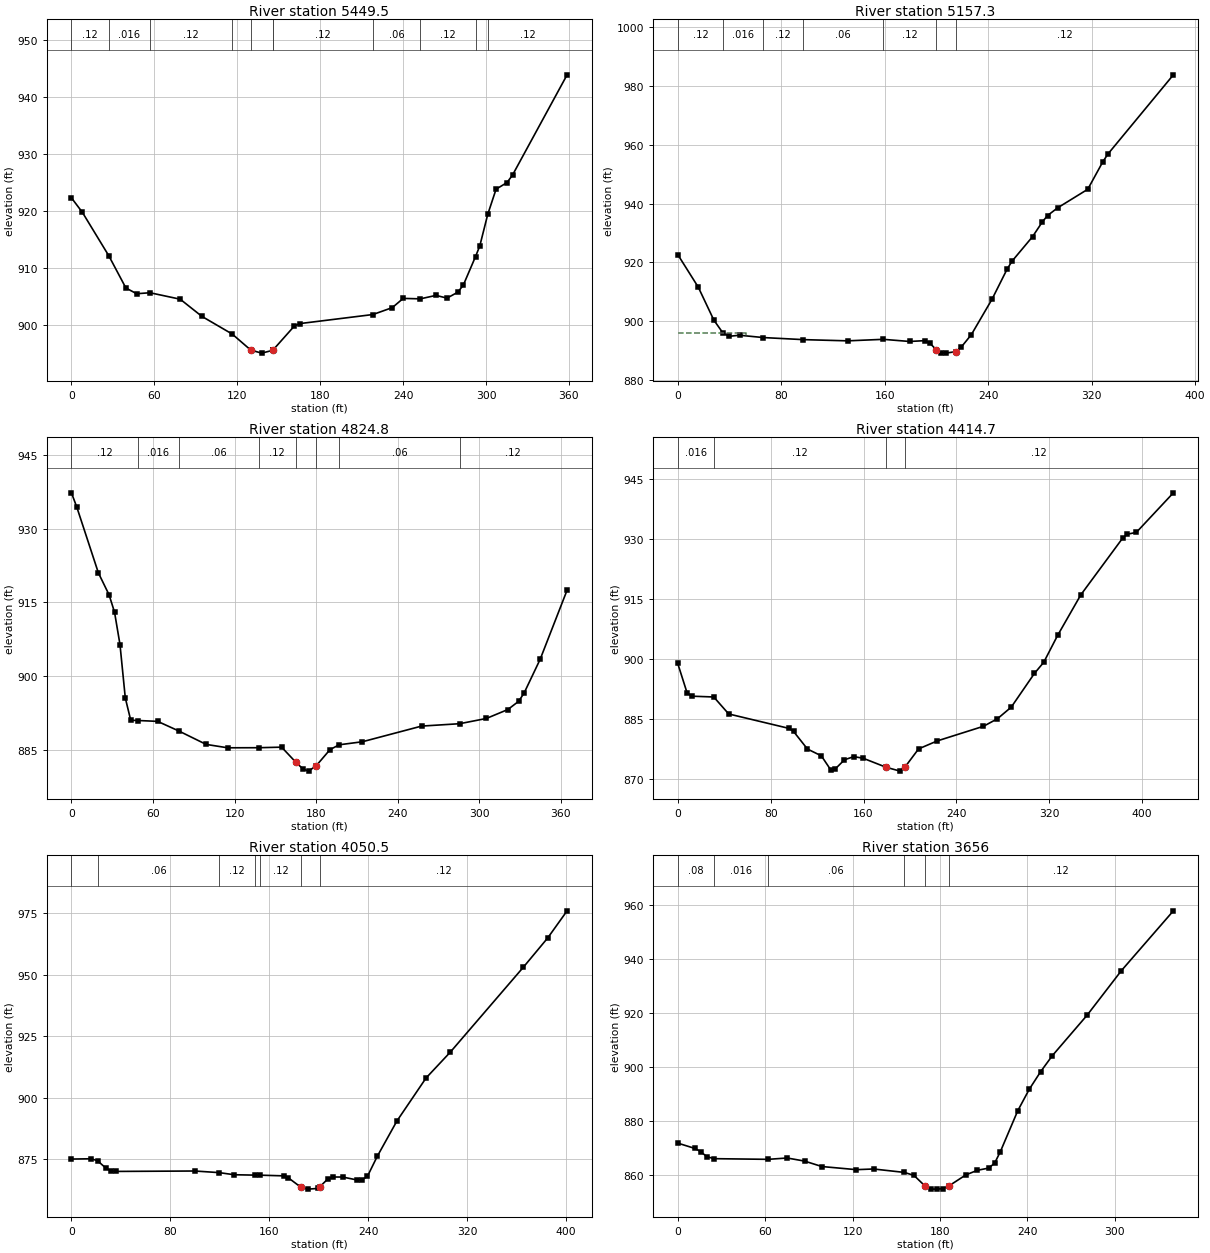
Type RM Length L Ch R = 1 ,5449.5  ,296.3,292.2,281.7
XS GIS Cut Line= 3
     1816587.276      363368.161      1816612.97      363575.105
     1816732.415      363666.077
#Sta/Elev= 30
       0  922.28     7.9  919.74   27.03912.1037    39.4  906.44    47.2  905.43
    56.8905.6052    78.7  904.47    94.4  901.45  116.32898.3461   129.8  895.52
   137.7  894.99   145.6  895.48  146.09895.5981   161.3  899.75   165.2  900.18
  218.17 901.775   232.2  902.99   240.1  904.61   252.5904.5313   263.8  905.14
   271.8  904.66   279.6   905.7   283.6  906.95  292.43911.9626   295.5  913.82
  301.25919.3651   307.3  923.81   315.2  924.97   319.2  926.29   358.7  943.91
#Mann= 11 ,-1 , 0
       0     .12       0   27.03    .016       0    56.8     .12       0
  116.32     .06       0   129.8    .045       0   145.6     .06       0
  146.09     .12       0  218.17     .06       0   252.5     .12       0
  292.43     .06       0  301.25     .12       0
Bank Sta=129.8,145.6
XS Rating Curve= 0 ,0
Exp/Cntr=0.3,0.1

Type RM Length L Ch R = 1 ,5157.3  ,325.4,332.5,339.5
XS GIS Cut Line= 3
     1816294.158       363420.51     1816368.811      363660.094
     1816434.783      363774.677
#Sta/Elev= 30
       0  922.65    15.9  911.53    27.9  900.35   35.15 895.825    39.8  894.82
    47.8  895.18   66.09  894.39   97.02893.6852   131.4  893.27   158.9893.7862
   179.2  893.06   191.2  893.34   195.2  892.37     200  890.18   203.2  889.28
   207.1  889.09     215  889.59   219.1  891.09     227  895.37     243  907.44
   254.8   917.8   258.7  920.51   274.3  928.71     282  933.81   285.9   935.9
   293.7  938.53     317  944.85   328.7  954.24   332.6  956.85   383.2   983.8
#Mann= 7 ,-1 , 0
       0     .12       0   35.15    .016       0   66.09     .12       0
   97.02     .06       0   158.9     .12       0     200    .045       0
     215     .12       0
#XS Ineff= 2 , 0
           52.43  896.01
Permanent Ineff=
       F       F
Bank Sta=200,215
XS Rating Curve= 0 ,0
Exp/Cntr=0.3,0.1

Type RM Length L Ch R = 1 ,4824.8  ,418.7,410.1,401.4
XS GIS Cut Line= 2
     1816053.248      363463.907     1816050.644       363828.49
#Sta/Elev= 30
       0  937.32       4  934.36    19.8  921.03    27.7  916.54    31.7  913.01
    35.7  906.44    39.6  895.58    43.6  891.02   49.24890.9641    63.4  890.79
   78.78888.8593    99.1   886.1   114.9  885.41  137.85885.4279   154.6  885.54
   165.1  882.46   170.4  881.08   174.4  880.66   180.1  881.77   190.2  885.04
  196.93 886.022     214  886.64   257.6  889.83  285.54890.3138   305.2  891.38
     321   893.2   328.9  894.86   332.9  896.52   344.8  903.44   364.6  917.51
#Mann= 8 ,-1 , 0
       0     .12       0   49.24    .016       0   78.78     .06       0
  137.85     .12       0   165.1    .045       0   180.1     .12       0
  196.93     .06       0  285.54     .12       0
Bank Sta=165.1,180.1
XS Rating Curve= 0 ,0
Exp/Cntr=0.3,0.1

Type RM Length L Ch R = 1 ,4414.7  ,365.9,364.2,362.4
XS GIS Cut Line= 2
     1815582.762      363543.334     1815738.144      363940.904
#Sta/Elev= 30
       0  898.93       8  891.61      12  890.73   31.03890.5275    43.9  886.28
    95.7  882.68    99.7  881.92   111.7  877.51   123.7   875.8   131.6  872.36
   135.6  872.52   143.6  874.82   151.6  875.61   159.6  875.21   179.5  872.94
   191.5  871.98   195.5  872.92   207.4  877.54   223.4  879.53   263.3   883.2
   275.3  885.08   287.2  887.99   307.2  896.44   315.2  899.22   327.1  905.92
   347.1  916.08     383  930.22     387  931.24   394.9   931.7   426.8   941.6
#Mann= 4 ,-1 , 0
       0    .016       0   31.03     .12       0   179.5    .045       0
   195.5     .12       0
Bank Sta=179.5,195.5
XS Rating Curve= 0 ,0
Exp/Cntr=0.3,0.1

Type RM Length L Ch R = 1 ,4050.5  ,394.8,394.5,393.8
XS GIS Cut Line= 3
     1815226.859      363671.372     1815339.706      363904.879
     1815347.519      364046.372
#Sta/Elev= 30
       0  875.06      16  875.18   21.12874.3707    27.9  871.35    31.9  870.25
    35.9  870.03    99.8   870.2  119.53869.5432   131.7  868.68  148.56868.5228
  152.34868.5111   171.6  868.23   175.6  867.38   185.9   863.5   191.5  862.83
   199.5  863.12   200.9  863.77   207.5  867.01   211.5  867.76   219.4  867.75
   231.4  866.52   235.4  866.73   239.4  867.97   247.4  876.15   263.3  890.53
   286.9  908.04   306.6   918.6   365.6  953.09   385.3  964.99     401  976.03
#Mann= 7 ,-1 , 0
       0    .016       0   21.12     .06       0  119.53     .12       0
  148.56     .06       0  152.34     .12       0   185.9    .045       0
   200.9     .12       0
Bank Sta=185.9,200.9
XS Rating Curve= 0 ,0
Exp/Cntr=0.3,0.1

Type RM Length L Ch R = 1 ,3656    ,367.4,379.6,391.6
XS GIS Cut Line= 2
     1814866.833      363812.269     1815020.479      364115.654
#Sta/Elev= 30
       0  871.85    11.9  869.85    15.8  868.69    19.8  866.88    24.7866.0825
   62.04865.8359    75.1  866.33      87  865.19    98.9  863.17   122.6  862.01
   134.4  862.26  155.45860.9944   162.1  859.89     170  855.79     174  854.82
     178   854.8   181.8  854.99   185.8  855.89   197.7  860.07   205.6  861.77
   213.5  862.61   217.5  864.48   221.4   868.7   233.3  883.81   241.2  891.78
   249.1  898.37     257  904.21   280.8  919.16   304.5  935.78   340.1  957.89
#Mann= 6 ,-1 , 0
       0     .08       0    24.7    .016       0   62.04     .06       0
  155.45     .12       0     170    .045       0   185.8     .12       0
Bank Sta=170,185.8
XS Rating Curve= 0 ,0
Exp/Cntr=0.3,0.1

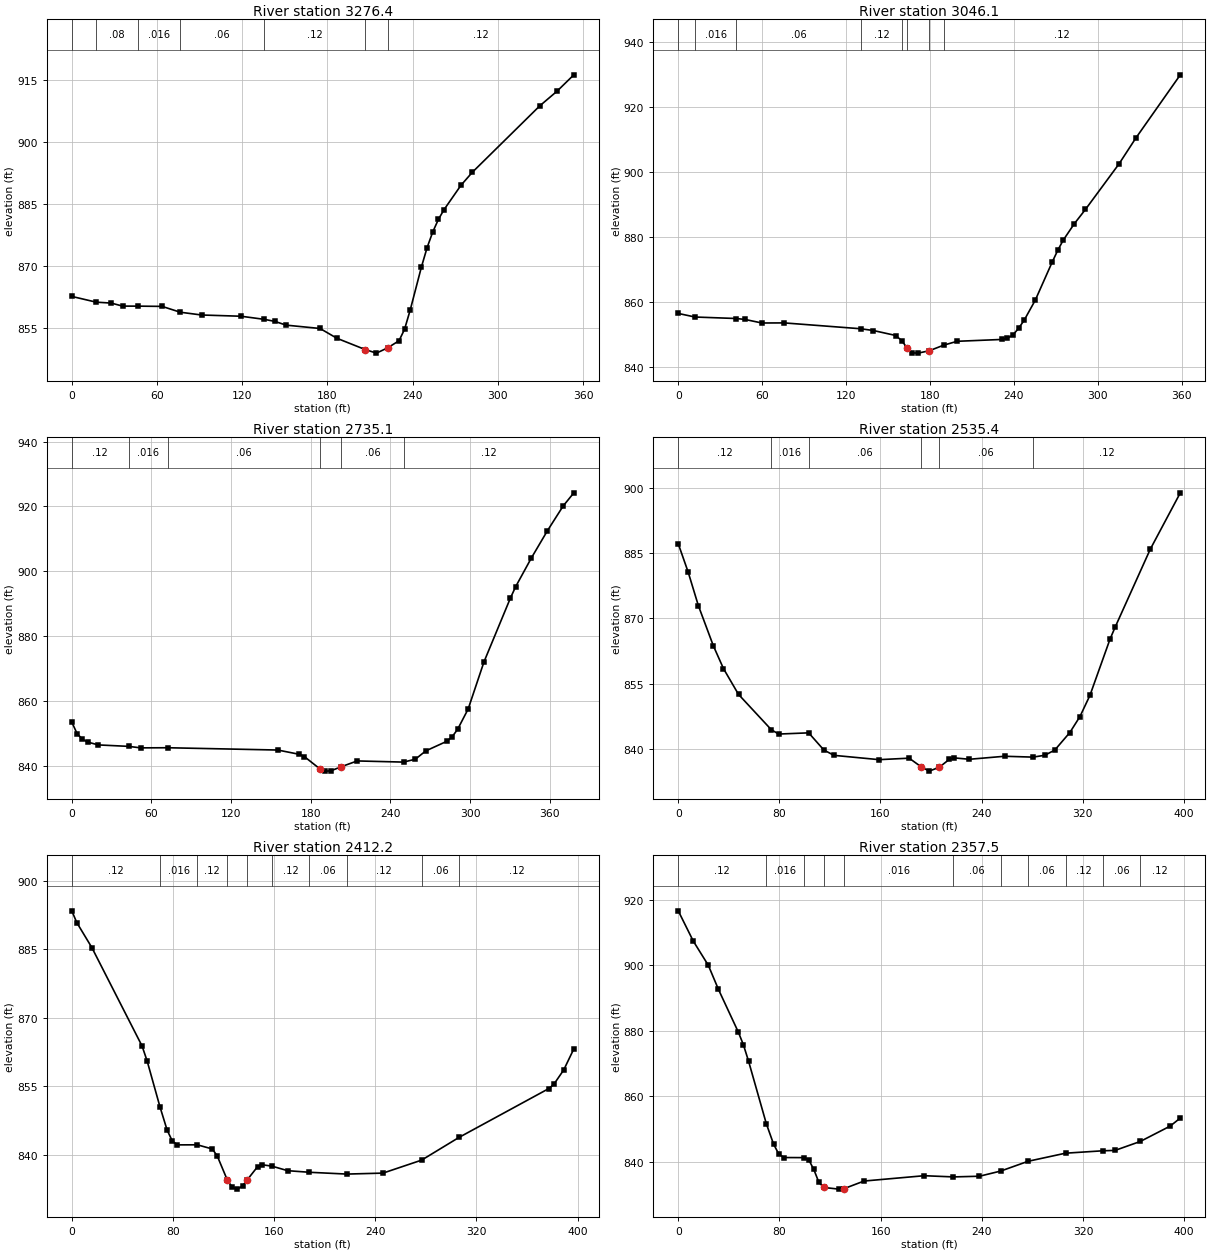
Type RM Length L Ch R = 1 ,3276.4  ,229.9,230.3,230.4
XS GIS Cut Line= 2
     1814603.812      363879.977     1814582.979      364232.842
#Sta/Elev= 30
       0  862.61   17.21 861.214    27.8  860.99    35.8  860.26    46.8860.2488
    63.6  860.19   76.39858.7744    91.4   858.1   119.2   857.8  135.56857.0436
     143  856.55   150.9  855.64   174.8  854.83   186.7  852.45   206.5  849.73
   214.5  848.85   222.4  850.13   230.4  851.85   234.3  854.63   238.3  859.33
   246.2  869.77   250.2  874.47   254.2  878.29   258.2  881.34   262.1  883.66
     274  889.56     282  892.72   329.6  908.87   341.6  912.38   353.5  916.37
#Mann= 7 ,-1 , 0
       0     .06       0   17.21     .08       0    46.8    .016       0
   76.39     .06       0  135.56     .12       0   206.5    .045       0
   222.4     .12       0
Bank Sta=206.5,222.4
XS Rating Curve= 0 ,0
Exp/Cntr=0.3,0.1

Type RM Length L Ch R = 1 ,3046.1  ,313.7,310.9,308
XS GIS Cut Line= 2
     1814378.552      363885.185      1814352.51      364243.258
#Sta/Elev= 30
       0  856.38   12.01855.2797   41.62854.8199    47.9  854.52    59.8  853.44
    75.8  853.47  130.47851.6696   139.6  851.12   155.6  849.59  160.08847.8719
   163.6  845.76   167.5  844.24   171.5  844.17   179.5   844.9   189.7 846.605
   199.4  847.81   231.4  848.38   235.4  848.72   239.4   849.8   243.3  851.78
   247.3  854.25   255.3  860.47   267.3   872.1   271.3  875.75   275.2  878.88
   283.2  883.98   291.2   888.4   315.1  902.35   327.1  910.28     359   929.8
#Mann= 8 ,-1 , 0
       0     .12       0   12.01    .016       0   41.62     .06       0
  130.47     .12       0  160.08     .06       0   163.6    .045       0
   179.5     .06       0   189.7     .12       0
Bank Sta=163.6,179.5
XS Rating Curve= 0 ,0
Exp/Cntr=0.3,0.1

Type RM Length L Ch R = 1 ,2735.1  ,200.3,199.8,199.4
XS GIS Cut Line= 2
     1814047.823      363883.883     1814068.656      364261.487
#Sta/Elev= 30
       0  853.53       4     850       8  848.26    11.9  847.39    19.9   846.5
   42.89846.0477    51.8  845.59   72.47845.6265   155.2  844.92   171.2  843.62
   175.2   842.9   187.1  839.05   191.1  838.42   195.1   838.5     203  839.78
     215  841.56  249.96841.2032   258.8   842.1   266.7  844.66   282.6  847.63
   286.6  849.06   290.6  851.27   298.6  857.58   310.5  872.09   330.4  891.75
   334.4   895.3   346.3  904.19   358.3  912.52   370.2  920.17   378.2   924.2
#Mann= 6 ,-1 , 0
       0     .12       0   42.89    .016       0   72.47     .06       0
   187.1    .045       0     203     .06       0  249.96     .12       0
Bank Sta=187.1,203
XS Rating Curve= 0 ,0
Exp/Cntr=0.3,0.1

Type RM Length L Ch R = 1 ,2535.4  ,120.6,123.2,124.6
XS GIS Cut Line= 2
     1813850.582       363882.75     1813871.415      364279.451
#Sta/Elev= 30
       0  887.19     7.9  880.62    15.9  872.96    27.8  863.68    35.8  858.45
    47.7  852.51    73.6844.3992    79.4  843.39  103.18843.6689   115.2  839.72
   123.2  838.49   158.9   837.5   182.7  837.84  192.43   835.8   198.6  834.86
   206.6  835.77   214.5  837.58   218.5   837.9   230.4  837.59   258.2  838.28
  280.64838.0831     290  838.51   297.9  839.71   309.8  843.74   317.8  847.42
   325.7  852.29   341.6  865.24   345.6  867.96   373.4   885.9   397.2   898.9
#Mann= 6 ,-1 , 0
       0     .12       0    73.6    .016       0  103.18     .06       0
  192.43    .045       0   206.6     .06       0  280.64     .12       0
Bank Sta=192.43,206.6
XS Rating Curve= 0 ,0
Exp/Cntr=0.3,0.1

Type RM Length L Ch R = 1 ,2412.2  ,54.4,54.6,55.9
XS GIS Cut Line= 2
     1813762.059      363886.661     1813743.309      364283.189
#Sta/Elev= 30
       0   893.4       4  890.81    15.9  885.34    55.6  863.78    59.6   860.5
   69.67850.5323    75.4  845.36    79.4  843.04    83.4  842.13   99.24842.1478
   111.2  841.23   115.1  839.66   123.1  834.36     127  832.82     131  832.44
     135  833.14   138.9  834.53   146.9  837.35   150.8  837.77  158.38837.4684
   170.7  836.48  187.94836.1298  217.51835.7362   246.1  835.95  276.65 838.795
  306.22843.7727   377.1  854.45   381.1  855.37     389  858.55     397  863.17
#Mann= 10 ,-1 , 0
       0     .12       0   69.67    .016       0   99.24     .12       0
   123.1    .045       0   138.9    .016       0  158.38     .12       0
  187.94     .06       0  217.51     .12       0  276.65     .06       0
  306.22     .12       0
Bank Sta=123.1,138.9
XS Rating Curve= 0 ,0
Exp/Cntr=0.3,0.1

Type RM Length L Ch R = 1 ,2357.5  ,102,102.4,102.5
XS GIS Cut Line= 2
     1813708.587      363886.661     1813689.837      364283.189
#Sta/Elev= 30
       0  916.58    11.9  907.33    23.8  899.93    31.8  892.57    47.6  879.46
    51.6  875.58    55.6  870.66   69.67851.5226    75.4   845.3    79.4  842.35
    83.4  841.21   99.24841.1833   103.2  840.52   107.2  837.56   111.2  833.64
   115.1  832.07     127  831.56     131  831.69   146.9  834.03   194.5  835.66
  217.52835.2921   238.2   835.5  255.05837.0896  276.65840.0663  306.22842.5387
  335.79843.2742   345.4  843.39  365.36846.1236     389  850.82     397  853.28
#Mann= 11 ,-1 , 0
       0     .12       0   69.67    .016       0   99.24     .06       0
   115.1    .045       0     131    .016       0  217.52     .06       0
  255.05    .016       0  276.65     .06       0  306.22     .12       0
  335.79     .06       0  365.36     .12       0
Bank Sta=115.1,131
XS Rating Curve= 0 ,0
Exp/Cntr=0.3,0.1

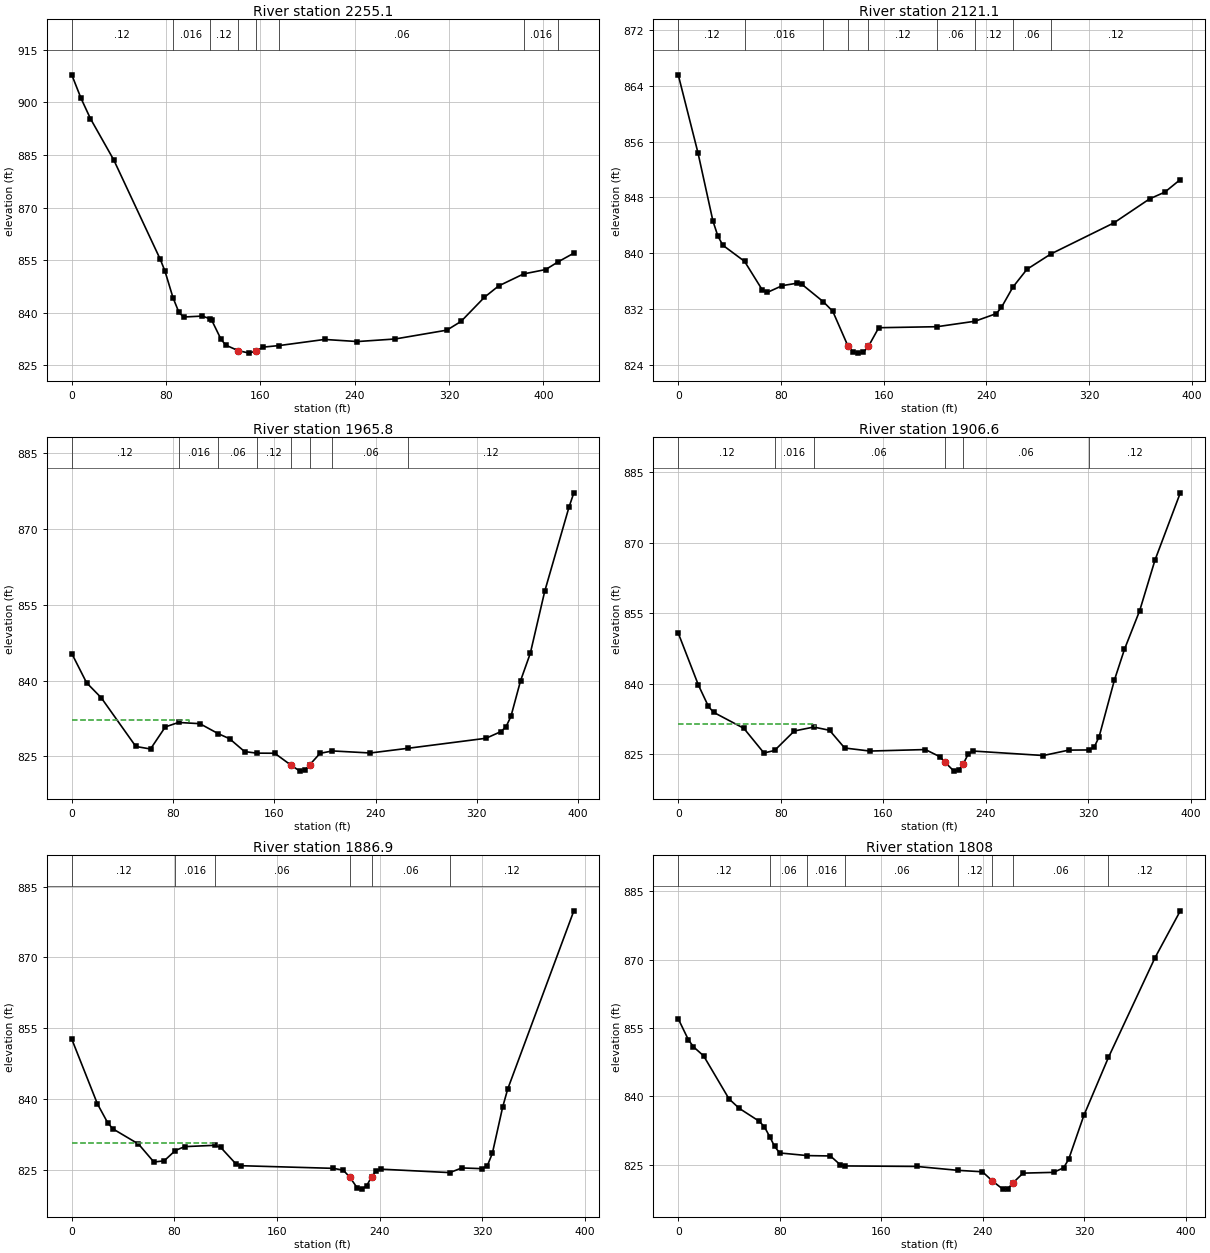
Type RM Length L Ch R = 1 ,2255.1  ,135.3,133.9,132.9
XS GIS Cut Line= 3
     1813643.117      363876.674     1813603.186      363975.632
     1813584.957      364294.208
#Sta/Elev= 30
       0  907.83     7.9   901.1    15.8  895.37    35.6  883.58    75.1  855.21
      79  851.92   85.81844.3474    90.9   840.1    94.8   838.8   110.7  839.07
  116.89838.3325   118.7  837.88   126.6  832.44   130.6  830.79   141.2  829.21
   150.6  828.51   156.2  829.15   162.6  830.23  176.06830.6741   214.4  832.41
   242.3  831.81   274.2  832.54   318.1  835.06   330.1  837.54     350  844.44
     362  847.66  383.15851.0781   401.9  852.33  412.73854.5781   425.8  857.01
#Mann= 8 ,-1 , 0
       0     .12       0   85.81    .016       0  116.89     .12       0
   141.2    .045       0   156.2     .12       0  176.06     .06       0
  383.15    .016       0  412.73     .12       0
Bank Sta=141.2,156.2
XS Rating Curve= 0 ,0
Exp/Cntr=0.3,0.1

Type RM Length L Ch R = 1 ,2121.1  ,159.1,155.4,151.7
XS GIS Cut Line= 3
      1813498.17      363877.633     1813468.309        363969.3
      1813466.92      364263.744
#Sta/Elev= 30
       0  865.57    15.4  854.37      27  844.64    30.8   842.5    34.7  841.16
   51.63838.8479    65.6  834.71    69.4   834.4      81  835.37    92.6  835.72
    96.4  835.54   112.9833.0695   120.3   831.7   132.2  826.69   136.2  825.86
   140.2   825.7   144.2  825.82   148.1  826.68   156.1  829.34  201.51829.4865
  231.05830.2693   247.6  831.36   251.6  832.24  260.59835.1672   271.5  837.71
  290.12839.9072   339.1  844.35     367   847.8   378.9  848.77   390.9  850.57
#Mann= 9 ,-1 , 0
       0     .12       0   51.63    .016       0   112.9     .12       0
   132.2    .045       0   148.1     .12       0  201.51     .06       0
  231.05     .12       0  260.59     .06       0  290.12     .12       0
Bank Sta=132.2,148.1
XS Rating Curve= 0 ,0
Exp/Cntr=0.3,0.1

Type RM Length L Ch R = 1 ,1965.8  ,54.7,59.2,61.3
XS GIS Cut Line= 4
     1813346.676      363847.811     1813304.141      363960.658
     1813339.731      364180.276     1813327.579      364232.359
#Sta/Elev= 30
       0  845.37    11.7  839.59    23.3  836.61    50.6  826.98    62.2  826.48
    73.9  830.85   84.33831.7302   101.2  831.49   115.9829.4841   124.6  828.52
   136.5  825.97  146.06825.6591   160.3  825.64  173.43  823.23   180.2   822.1
   184.2  822.27   188.1  823.39   196.1  825.62  205.91826.0957   235.8  825.69
  265.75 826.625   327.2   828.6   339.1  829.93   343.1  830.92   346.9  832.92
   354.5  839.98   362.2  845.41   373.6  857.69   392.7  874.28   396.6  877.17
#Mann= 8 ,-1 , 0
       0     .12       0   84.33    .016       0   115.9     .06       0
  146.06     .12       0  173.43    .045       0   188.1     .12       0
  205.91     .06       0  265.75     .12       0
#XS Ineff= 2 , 0
           92.88  832.26
Permanent Ineff=
       F       F
Bank Sta=173.43,188.1
XS Rating Curve= 0 ,0
Exp/Cntr=0.3,0.1

Type RM Length L Ch R = 1 ,1906.6  ,19.2,19.7,19.2
XS GIS Cut Line= 4
     1813305.443       363824.59     1813254.228      364014.694
       1813257.7      364051.153     1813207.353      364201.326
#Sta/Elev= 30
       0  850.73    15.8  839.63    23.6  835.11    27.6  833.87    51.2  830.47
    66.9  825.22   75.19825.7526    90.6   829.9  105.78830.7386   118.1  830.05
   129.9  826.28   149.6  825.63   192.9  825.95   204.2  824.43   207.9  823.34
   215.2  821.36   218.9  821.55   222.5  822.92   226.2  824.91   229.8  825.64
     285  824.68   304.8  825.83  320.34825.8654   324.6  826.42   328.5  828.65
   340.4  840.68   348.3  847.27   360.2  855.51   372.1  866.23   391.9  880.57
#Mann= 6 ,-1 , 0
       0     .12       0   75.19    .016       0  105.78     .06       0
   207.9    .045       0   222.5     .06       0  320.34     .12       0
#XS Ineff= 2 , 0
          106.91  831.35
Permanent Ineff=
       F       F
Bank Sta=207.9,222.5
XS Rating Curve= 0 ,0
Exp/Cntr=0.3,0.1

Type RM Length L Ch R = 1 ,1886.9  ,78.2,78.9,82.8
XS GIS Cut Line= 4
     1813289.837        363819.3     1813235.131      364019.903
     1813238.603      364056.361     1813192.614      364195.689
#Sta/Elev= 30
       0   852.7      20  838.98      28  834.98      32   833.7      52  830.48
      64  826.67      72  826.92   80.73829.1105      88  829.93  111.35830.2084
     116  829.79     128  826.25     132  825.89   203.9  825.33   211.6  824.94
   216.7  823.46   222.6  821.14   226.2  820.93   229.9  821.67   233.6   823.5
   237.2  824.81   240.9  825.16  294.66824.4288     304  825.42   319.9  825.26
   323.9   825.9   327.8  828.52   335.8  838.28   339.7  842.08   391.3  879.87
#Mann= 6 ,-1 , 0
       0     .12       0   80.73    .016       0  111.35     .06       0
   216.7    .045       0   233.6     .06       0  294.66     .12       0
#XS Ineff= 2 , 0
          111.04  830.64
Permanent Ineff=
       F       F
Bank Sta=216.7,233.6
XS Rating Curve= 0 ,0
Exp/Cntr=0.3,0.1

Type RM Length L Ch R = 1 ,1808    ,232.3,237.1,241.9
XS GIS Cut Line= 2
     1813180.877      363795.727     1813147.023      364189.825
#Sta/Elev= 30
       0     857       8  852.39      12  850.84      20  848.86      40  839.42
      48  837.35    63.9  834.49    67.9  833.27   72.19831.0683    75.9     829
    79.9  827.55  101.84 826.967   119.9  826.89   127.8  824.92  131.48824.6992
   187.8  824.59  220.42823.7325   239.7  823.42   247.5  821.41   255.7  819.61
   259.7  819.71   263.7  820.97   271.7  823.12   295.7  823.29   303.6  824.28
   307.6  826.14   319.6  835.78     339848.5355   375.6  870.36   395.6  880.69
#Mann= 8 ,-1 , 0
       0     .12       0   72.19     .06       0  101.84    .016       0
  131.48     .06       0  220.42     .12       0   247.5    .045       0
   263.7     .06       0     339     .12       0
Bank Sta=247.5,263.7
XS Rating Curve= 0 ,0
Exp/Cntr=0.3,0.1

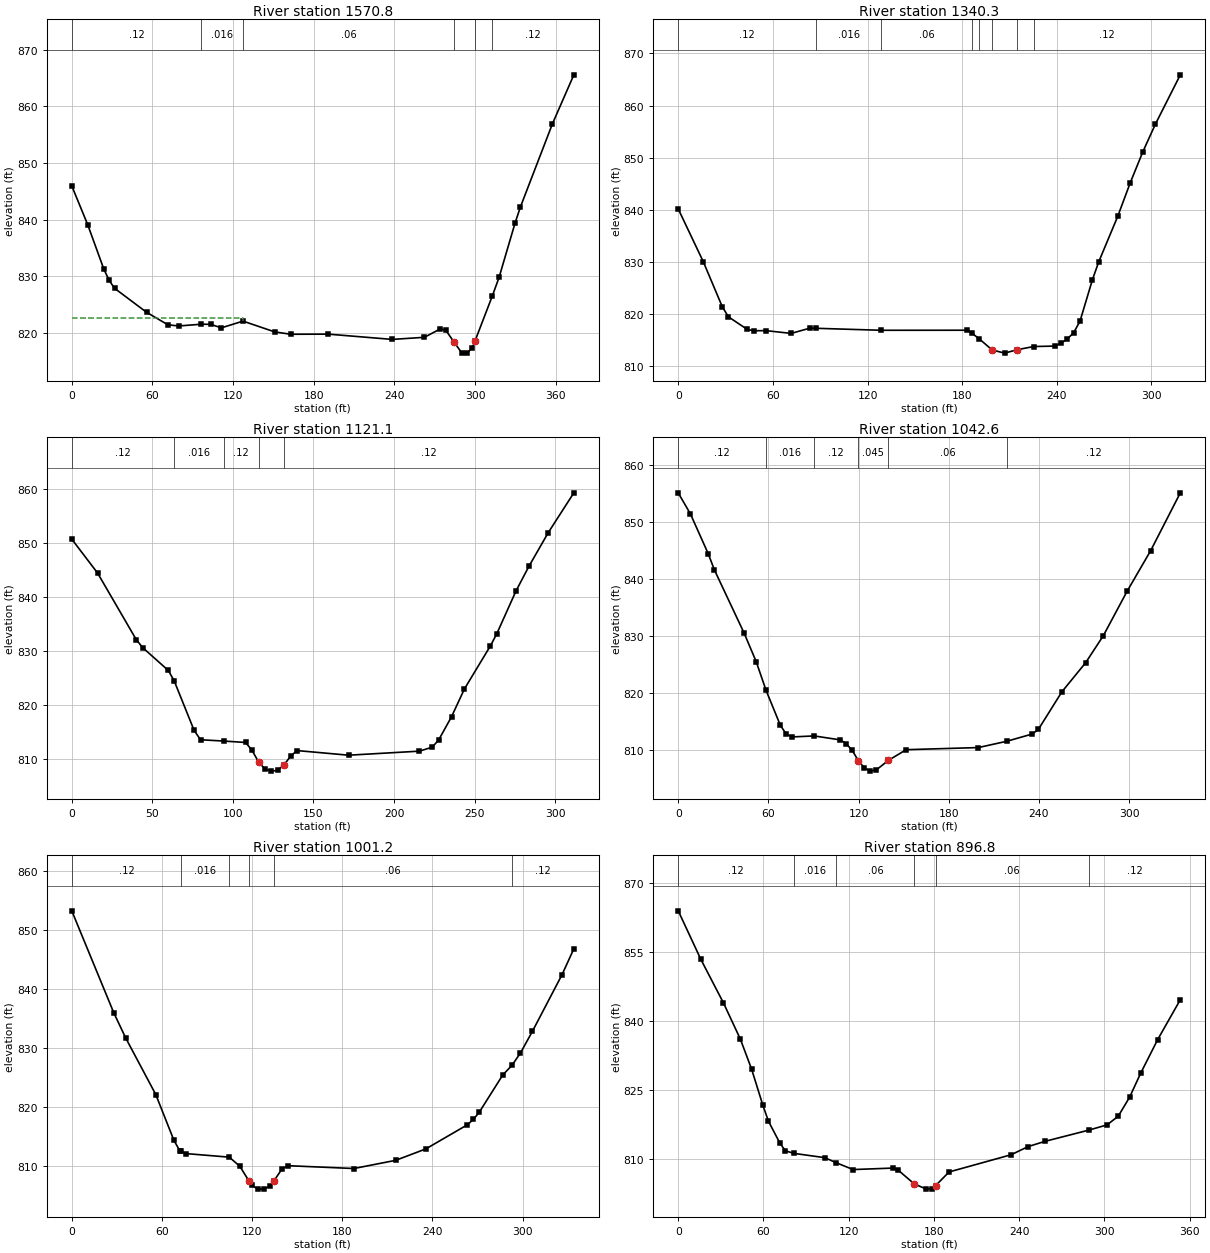
Type RM Length L Ch R = 1 ,1570.8  ,232.6,230.5,226.6
XS GIS Cut Line= 2
     1813010.855      363745.978     1812900.178      364102.749
#Sta/Elev= 30
       0  845.95    11.9  839.08    23.8   831.3    27.8  829.29    31.8  827.89
    55.6  823.66    71.5  821.45    79.5  821.24   96.48821.5497   103.3  821.53
   111.3  820.91   127.4822.0953     151  820.19   162.9  819.78   190.8   819.8
   238.4  818.87   262.3  819.24   274.2  820.73   278.2   820.5  284.23  818.45
   290.1   816.5   294.1  816.45     298  817.43   300.1  818.67  312.95826.5959
   317.9  829.83   329.8  839.42   333.8  842.26   357.6  856.92   373.5  865.54
#Mann= 6 ,-1 , 0
       0     .12       0   96.48    .016       0   127.4     .06       0
  284.23    .045       0   300.1     .06       0  312.95     .12       0
#XS Ineff= 2 , 0
          127.55  822.57
Permanent Ineff=
       F       F
Bank Sta=284.23,300.1
XS Rating Curve= 0 ,0
Exp/Cntr=0.3,0.1

Type RM Length L Ch R = 1 ,1340.3  ,216.6,219.2,222.8
XS GIS Cut Line= 2
     1812876.671      363703.929     1812712.782      363976.846
#Sta/Elev= 30
       0  840.18    15.9  830.05    27.9  821.45    31.8   819.5    43.8  817.08
    47.8  816.83    55.7  816.85    71.6  816.32    83.6  817.34   87.63817.2987
  128.65816.9196     183  816.93  186.02816.4091  190.99815.2325     199  813.15
   206.9  812.54   214.9   813.2  225.44813.8062   238.8  813.89   242.7  814.45
   246.7  815.26   250.7  816.47   254.7  818.66   262.6  826.63   266.6  830.06
   278.6  838.74   286.5  845.15   294.5  851.11   302.4  856.37   318.3  865.89
#Mann= 8 ,-1 , 0
       0     .12       0   87.63    .016       0  128.65     .06       0
  186.02     .12       0  190.99     .06       0     199    .045       0
   214.9     .06       0  225.44     .12       0
Bank Sta=199,214.9
XS Rating Curve= 0 ,0
Exp/Cntr=0.3,0.1

Type RM Length L Ch R = 1 ,1121.1  ,76.2,78.5,80.8
XS GIS Cut Line= 2
     1812660.391      363629.755     1812568.377      363927.498
#Sta/Elev= 30
       0   850.8      16  844.53      40   832.2      44  830.71    59.9  826.48
   63.53824.5743    75.9   815.4    79.9  813.64   94.44   813.4   107.9  813.14
   111.9  811.67   115.9  809.54   119.9  808.22   123.9  807.83   127.8  807.98
   131.8     809   135.8  810.61   139.8  811.64   171.8  810.78   215.8  811.53
   223.7  812.27   227.7   813.6   235.7  817.91   243.7  823.06   259.7  830.97
   263.7  833.23   275.7   841.2   283.7  845.76   295.7     852   311.6  859.38
#Mann= 5 ,-1 , 0
       0     .12       0   63.53    .016       0   94.44     .12       0
   115.9    .045       0   131.8     .12       0
Bank Sta=115.9,131.8
XS Rating Curve= 0 ,0
Exp/Cntr=0.3,0.1

Type RM Length L Ch R = 1 ,1042.6  ,41.5,41.4,41.6
XS GIS Cut Line= 3
     1812598.759      363607.186     1812505.009      363827.672
     1812514.279        363921.7
#Sta/Elev= 30
       0  855.16       8  851.54      20  844.48      24   841.7    43.9  830.55
    51.9  825.56   58.38820.5914    67.9  814.44    71.9  812.86    75.9  812.38
   90.48812.5499   107.8  811.86   111.8   811.2   115.8     810   119.8  808.24
   123.8  806.95   127.8  806.38   131.8  806.59   139.8  808.26   151.7  810.14
   199.7  810.51  218.86811.6323   235.6  812.89   239.6  813.68   255.3  820.29
   271.1  825.39   282.9  830.14   298.6  837.88   314.4  845.05   334.1  855.18
#Mann= 6 ,-1 , 0
       0     .12       0   58.38    .016       0   90.48     .12       0
   119.8    .045       0   139.8     .06       0  218.86     .12       0
Bank Sta=119.8,139.8
XS Rating Curve= 0 ,0
Exp/Cntr=0.3,0.1

Type RM Length L Ch R = 1 ,1001.2  ,111.5,104.4,96.2
XS GIS Cut Line= 3
     1812559.523      363593.991     1812465.773      363814.477
     1812475.043      363908.506
#Sta/Elev= 30
       0  853.21      28  835.92    35.9  831.67    55.9   822.1    67.9  814.39
    71.9  812.55   72.72812.4578    75.9   812.1  104.82811.4944   111.8  809.96
  117.72  807.54   119.7  806.76   123.8  806.08   127.8  806.09   131.8  806.58
   134.7  807.54   139.8  809.46   143.8  810.05   187.7  809.57   215.6  810.96
   235.6  812.89   263.2  816.97   267.2  817.88   271.1  819.08   286.8  825.41
  293.04827.0833   298.6  829.15   306.5  832.79   326.2  842.38   334.1  846.78
#Mann= 6 ,-1 , 0
       0     .12       0   72.72    .016       0  104.82     .06       0
  117.72    .045       0   134.7     .06       0  293.04     .12       0
Bank Sta=117.72,134.7
XS Rating Curve= 0 ,0
Exp/Cntr=0.3,0.1

Type RM Length L Ch R = 1 ,896.8   ,314.9,326,337.5
XS GIS Cut Line= 2
     1812417.643      363549.763      1812396.81      363902.541
#Sta/Elev= 30
       0  864.03    15.9  853.45    31.8  843.96    43.7  836.06    51.6  829.54
    59.6  821.58    63.5  818.14    71.5  813.38    75.4  811.67   81.76811.1041
   103.2  810.18  111.35809.0538   123.1  807.59   150.9  807.91   154.9  807.44
   166.1  804.46   174.7  803.32   178.7  803.44   181.1  804.06   190.6  807.06
   234.3  810.82   246.2  812.59   258.1  813.74  288.88816.1831   301.8  817.33
   309.7  819.22   317.7  823.37   325.6  828.67   337.5  835.96   353.4  844.64
#Mann= 6 ,-1 , 0
       0     .12       0   81.76    .016       0  111.35     .06       0
   166.1    .045       0   181.1     .06       0  288.88     .12       0
Bank Sta=166.1,181.1
XS Rating Curve= 0 ,0
Exp/Cntr=0.3,0.1

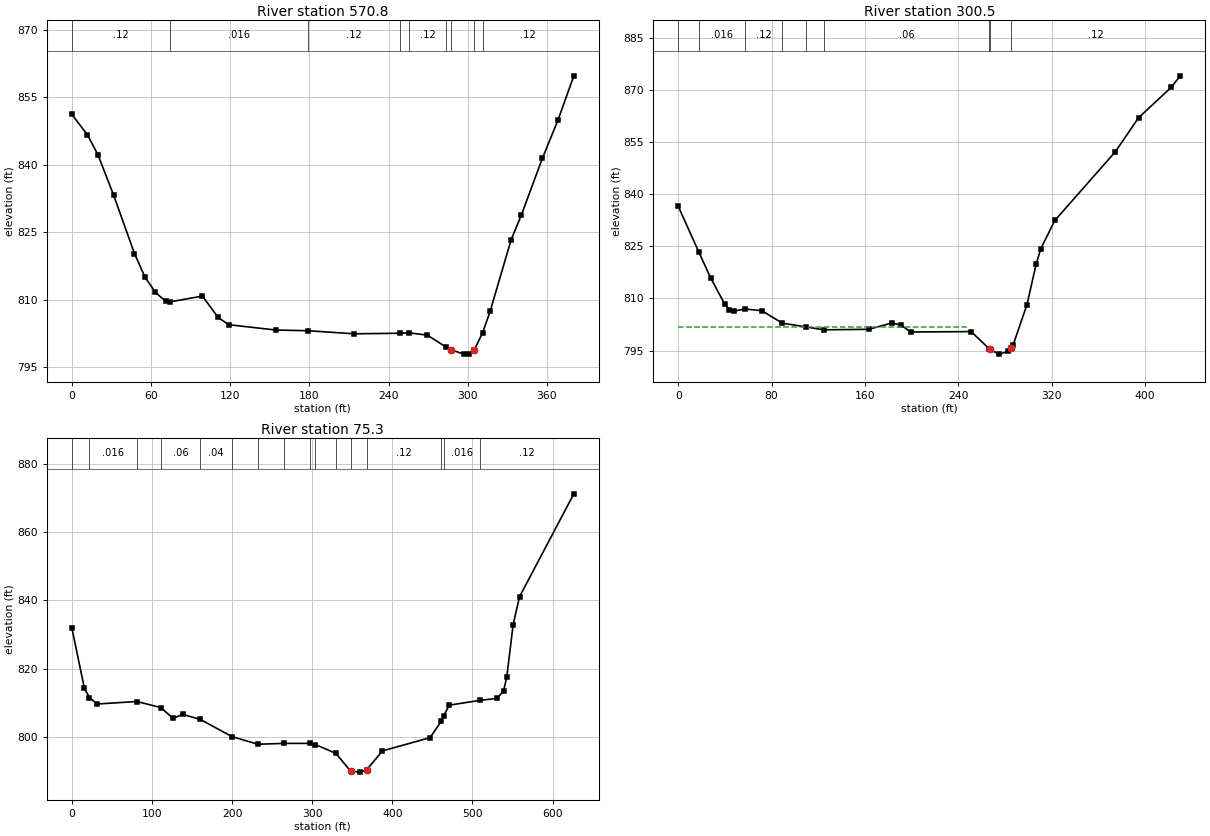
Type RM Length L Ch R = 1 ,570.8   ,269.2,270.4,271
XS GIS Cut Line= 2
     1812266.949      363538.652     1812064.866      363860.874
#Sta/Elev= 30
       0   851.2    11.9  846.62    19.8  842.23    31.7  833.25    47.5  820.28
    55.5  815.04    63.4  811.66    71.3  809.66    74.6809.5692      99  810.84
   110.9   806.1   118.9  804.49   154.5  803.31  179.19803.1486     214  802.47
  248.92802.5949  255.69802.6807   269.4  802.17  283.79799.5016   287.7  798.88
   297.2  797.96   301.1  798.09   305.1  798.98  311.28802.7075     317  807.49
   332.8  823.26   340.7  828.88   356.6  841.45   368.5  849.99   380.4  859.73
#Mann= 9 ,-1 , 0
       0     .12       0    74.6    .016       0  179.19     .12       0
  248.92     .06       0  255.69     .12       0  283.79     .06       0
   287.7    .045       0   305.1     .06       0  311.28     .12       0
Bank Sta=287.7,305.1
XS Rating Curve= 0 ,0
Exp/Cntr=0.3,0.1

Type RM Length L Ch R = 1 ,300.5   ,228.7,225.2,220.9
XS GIS Cut Line= 2
     1812045.421      363410.179     1811802.366      363765.041
#Sta/Elev= 30
       0   836.5   17.52823.4283    27.9  815.81    39.8  808.38    43.8  806.76
    47.8  806.38   57.47  806.96    71.7  806.46   89.12802.8964  109.74801.7796
  124.92800.9727   163.3  801.12   183.2  802.97   191.2  802.26   199.1  800.34
   250.9  800.46  266.54795.4669   266.8  795.36   274.8  793.98   282.8   794.8
  284.91  795.72   286.8  796.54   298.7  808.16   306.7     820   310.6  824.31
   322.6  832.43   374.4  852.17   394.3  861.96   422.2  870.69   430.1  874.03
#Mann= 9 ,-1 , 0
       0     .12       0   17.52    .016       0   57.47     .12       0
   89.12     .06       0  109.74     .08       0  124.92     .06       0
  266.54     .12       0   266.8    .045       0  284.91     .12       0
#XS Ineff= 2 , 0
          246.65  801.79
Permanent Ineff=
       F       F
Bank Sta=266.8,284.91
XS Rating Curve= 0 ,0
Exp/Cntr=0.3,0.1

Type RM Length L Ch R = 1 ,75.3    ,81.8,75.3,69.3
XS GIS Cut Line= 4
     1811916.862      363320.423      1811790.56      363328.235
     1811666.988      363602.368      1811790.56      363758.791
#Sta/Elev= 30
       0  832.03    15.8  814.16   22.11 811.493    31.6  809.61   81.29810.3439
  110.89808.5796   126.5  805.42   138.4  806.58  160.39805.0872  199.89800.0674
  232.26797.8166  264.69798.0708  297.09 798.075  304.13797.7106  329.49795.1722
   348.1  789.91     360  789.65   367.9  790.29   387.7  795.87   447.2  799.76
  461.21804.5719  464.24806.2169   471.1  809.27  508.86810.6572   530.9  811.26
   538.9  813.48   542.9  817.49   550.8  832.85   558.8  841.05   626.6   871.2
#Mann= 16 ,-1 , 0
       0     .12       0   22.11    .016       0   81.29     .08       0
  110.89     .06       0  160.39     .04       0  199.89     .06       0
  232.26     .04       0  264.69     .06       0  297.09     .12       0
  304.13     .04       0  329.49     .12       0   348.1    .045       0
   367.9     .12       0  461.21     .08       0  464.24    .016       0
  508.86     .12       0
Bank Sta=348.1,367.9
XS Rating Curve= 0 ,0
Exp/Cntr=0.3,0.1

Chan Stop Cuts=-1
Use User Specified Reach Order=0
Composite Channel Slope=5